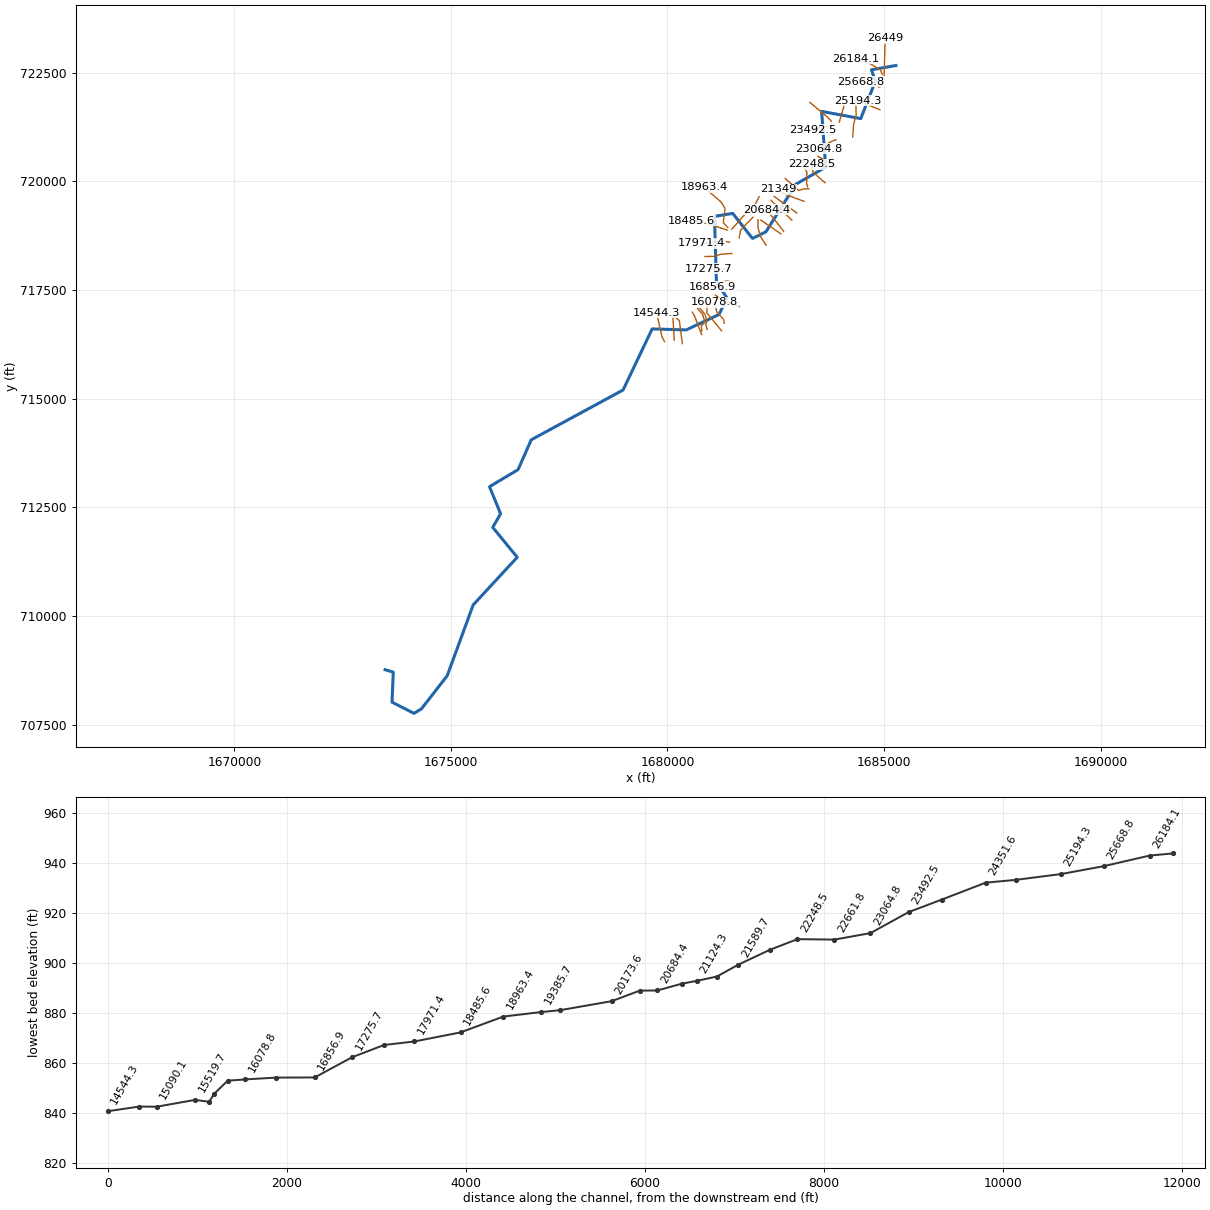
--- NFKINGSCK.prj (project) ---

Proj Title=NFKINGSCK
Current Plan=p01
Default Exp/Contr=0,0
English Units
Geom File=g01
Geom File=g09
Flow File=f01
Plan File=p01
BEGIN DESCRIPTION:
END DESCRIPTION:
DSS Export Rating Curves= 0
DSS Export Rating Curve Sorted= 0
DSS Export Volume Flow Curves= 0
DXF Filename=..\..\..\..\..\Engineering\Hydraulics\NFKINGSCK\NFKINGSCK.
DXF OffsetX= 0
DXF OffsetY= 0
DXF ScaleX= 0
DXF ScaleY= 0

--- NFKINGSCK.p01 (plan) ---

Plan Title=Floodplain
Program Version=4.00
Geom File=g01
Flow File=f01
K Sum by GR=0
Std Step Tol=0.01
Critical Tol=0.01
Num of Std Step Trials=20
Max Error Tol=0.3
Flow Tol Ratio=0.001
Split Flow NTrial=30
Split Flow Tol=0.02
Split Flow Ratio=0.02
Log Output Level=0
Friction Slope Method=1
Unsteady Friction Slope Method=2
Unsteady Bridges Friction Slope Method=1
Global Log Level=0
CheckData=False
Run HTab=0
Run UNet=0
Run PostProcess=0
UNET Theta=0
UNET Theta Warmup=0
UNET ZTol=0
UNET ZSATol=0
UNET MxIter=0
UNET MaxInSteps=0
UNET DtIC=0
UNET DtMin=0
UNET MaxCRTS=0
UNET WFStab=0
UNET SFStab=0
UNET WFX=0
UNET SFX=0
UNET DSS MLevel=0
UNET DZMax Abort=0
UNET Convert EG Bridges=0
UNET Use Existing IB Tables=0
UNET Froude Limit=0
UNET Froude Power=0
Write IC File=0
Echo Input=False
Echo Output=False
Write Detailed=0

--- NFKINGSCK.f01 (steady flow) ---

Flow Title=NFF Regression Equation
Program Version=4.10
Number of Profiles= 1
Profile Names=P100yr
River Rch & RM=NFKINGSCK,Main            ,26449
  2330.9
River Rch & RM=NFKINGSCK,Main            ,22248.5
2466.333
River Rch & RM=NFKINGSCK,Main            ,18963.4
2546.941
River Rch & RM=NFKINGSCK,Main            ,18485.6
2946.025
River Rch & RM=NFKINGSCK,Main            ,12975.8
3129.349
Boundary for River Rch & Prof#=NFKINGSCK,Main            , 1
Up Type= 0
Dn Type= 1
Dn Known WS=778
DSS Import GetInterval= 0
DSS Import GetPeak= 0
DSS Import FillOption= 0

--- NFKINGSCK.g01 (geometry) ---

Geom Title=2003 WVU SAMB 3 Meter DEM
Program Version=4.10

River Reach=NFKINGSCK       ,Main
Reach XY= 30
     1685275.531      722661.213     1684710.427      722562.255
     1684798.968      722299.234     1684463.031      721439.859
     1683559.385      721606.526     1683653.135      720325.276
     1682964.852      719930.626     1682273.345      718836.826
     1681962.453       718683.48     1681506.655      719260.558
     1681084.639      719190.933      1681130.98      717681.928
     1681372.766      717317.731     1681191.722      716936.286
     1680432.421      716580.058     1679646.158      716602.931
     1678975.309       715198.55     1676854.945      714053.613
     1676549.844      713366.223      1675890.98      712974.964
     1676147.269      712352.291     1675964.977      712039.878
     1676531.215      711351.876     1675514.167      710256.139
     1674913.788      708626.052     1674320.608      707867.164
     1674146.456      707761.538     1673640.486      708019.992
     1673668.872      708709.661     1673481.128      708766.497

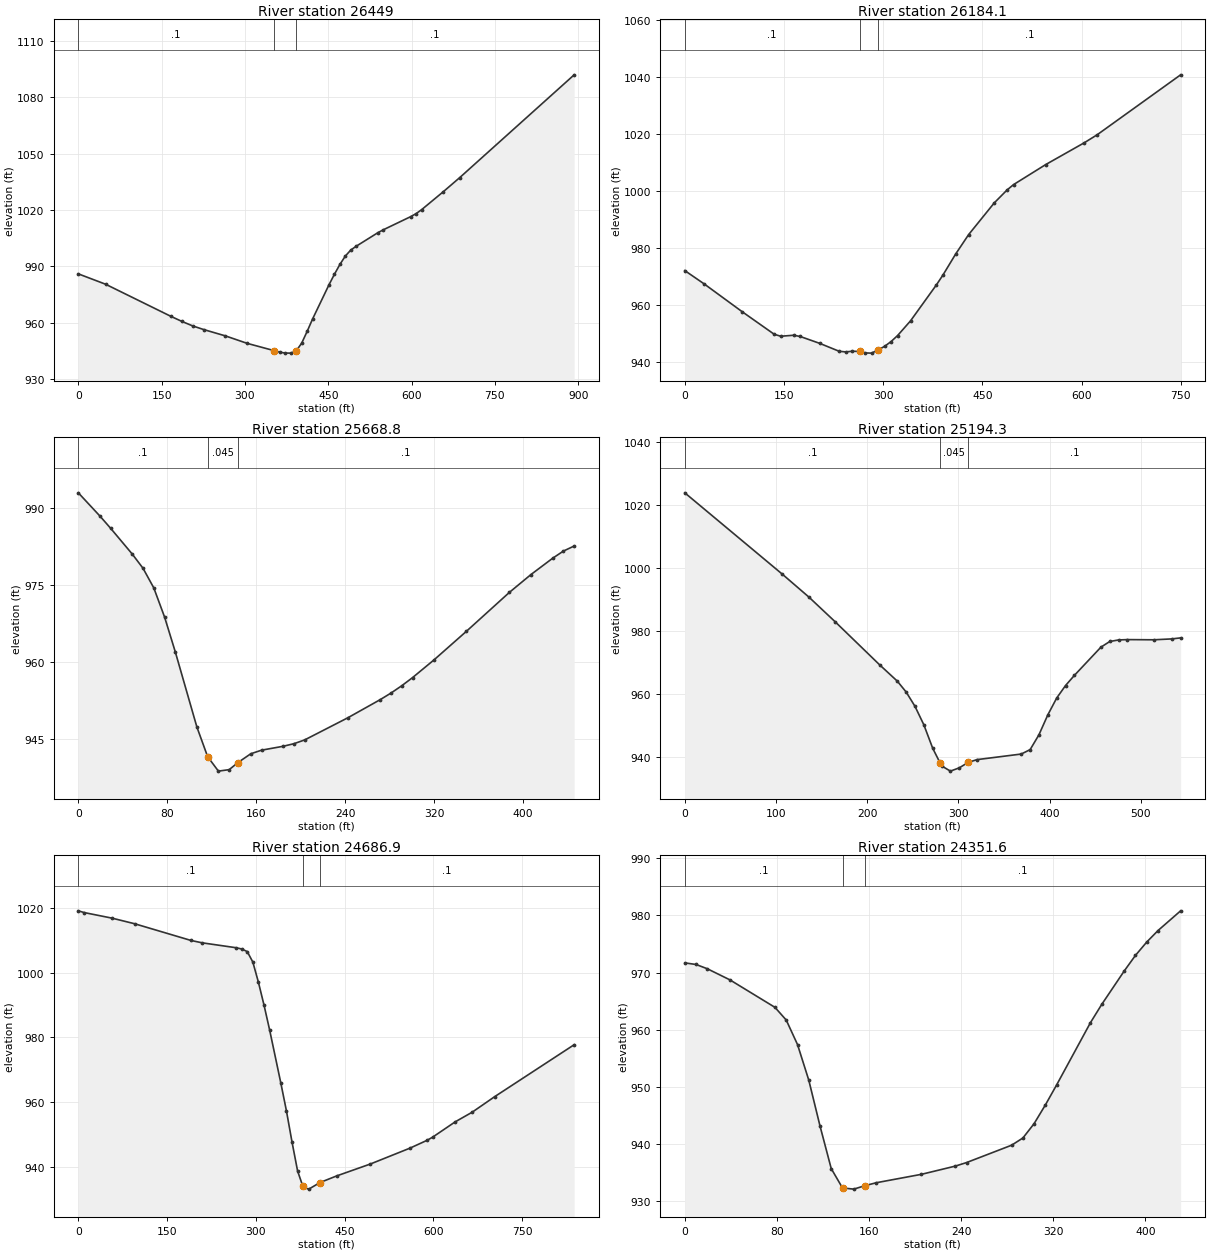
Type RM Length L Ch R = 1 ,26449   ,22307.3,265,22252.7
XS GIS Cut Line= 2
     1685002.035      722393.678     1685026.341      723286.039
#Sta/Elev= 30
       0  986.02      49  980.52   166.8   963.4   186.4  960.73     206  958.32
   225.6   956.4   264.9  953.01   304.1  949.04   351.8  945.23     363  944.32
   372.8  943.89   382.6  943.85   392.4  945.08   402.2  949.19     412  955.45
   421.8  962.05   451.2  980.16   461.1  985.82   470.9  991.02   480.7  995.49
   490.5  998.69   500.3 1000.73   539.5 1007.96   549.4 1009.52   598.4 1016.47
   608.2 1018.09     618 1020.16   657.3 1029.78   686.7 1037.24   892.7 1091.92
#Mann= 3 , 0 , 0
       0      .1       0   351.8    .045       0   392.4      .1       0
Bank Sta=351.8,392.4
XS Rating Curve= 0 ,0
Exp/Cntr=0.3,0.1

Type RM Length L Ch R = 1 ,26184.1 ,22307.3,515.3,22252.7
XS GIS Cut Line= 4
     1684960.369      722459.651     1684918.702      722556.873
     1684693.008      722695.762     1684335.369      722820.762
#Sta/Elev= 30
       0  972.02    28.8  967.42    86.5   957.6   135.2  949.62     145  948.93
   164.7  949.28   174.5  948.84   203.9  946.43   233.4  943.64   243.2  943.42
     253  943.65   264.3  943.59   272.6  943.06   282.4  942.99   292.3  944.13
   302.1  945.38   311.9  947.07   321.7  949.17   341.3  954.35   380.5  967.03
   390.2  970.43   409.6  977.89   429.1  984.68   467.9  995.85   487.4 1000.42
   497.1 1002.28   545.6 1009.31   603.9 1016.98   623.4 1019.79   749.6 1040.88
#Mann= 3 , 0 , 0
       0      .1       0   264.3    .045       0   292.3      .1       0
Bank Sta=264.3,292.3
XS Rating Curve= 0 ,0
Exp/Cntr=0.3,0.1

Type RM Length L Ch R = 1 ,25668.8 ,22307.3,474.4,22252.7
XS GIS Cut Line= 2
     1684901.341      722164.512     1684474.258      722292.984
#Sta/Elev= 30
       0  992.95    19.4  988.43    29.1  986.03    48.5  981.02    58.2  978.25
    67.9  974.42    77.6  968.74    87.3  961.91   106.6  947.36   116.3  941.56
     126  938.74   135.7  939.03   143.6  940.41   155.1  942.12   164.8  942.82
   184.2  943.58   193.9  944.08   203.6  944.82   242.4  949.13   271.5  952.66
   281.2  953.94   290.9  955.37   300.6  956.95     320  960.42     349  965.96
   387.8  973.57   407.2  977.04   426.6   980.2   436.3   981.6     446  982.59
#Mann= 3 , 0 , 0
       0      .1       0   116.3    .045       0   143.6      .1       0
Bank Sta=116.3,143.6
XS Rating Curve= 0 ,0
Exp/Cntr=0.3,0.1

Type RM Length L Ch R = 1 ,25194.3 ,22307.3,507.4,22252.7
XS GIS Cut Line= 2
     1684904.813      721643.678     1684401.341      721848.539
#Sta/Elev= 30
       0 1023.75   106.8  998.01   135.9  990.77     165  982.87   213.5   969.3
     233   964.1   242.7  960.65   252.4  956.11   262.1  950.26   271.8  942.84
     280  938.13   281.5  937.27   291.2   935.6   300.9  936.64   310.6  938.35
   320.3  939.24   368.8  941.01   378.6  942.41   388.2  947.07     398  953.42
   407.7  958.74   417.4   962.7   427.1  965.92   456.2  974.86   465.9  976.66
   475.6  977.15   485.3  977.26   514.4   977.2   533.8  977.48   543.6   977.8
#Mann= 3 , 0 , 0
       0      .1       0     280    .045       0   310.6      .1       0
Bank Sta=280,310.6
XS Rating Curve= 0 ,0
Exp/Cntr=0.3,0.1

Type RM Length L Ch R = 1 ,24686.9 ,22307.3,335.4,22252.7
XS GIS Cut Line= 4
     1684276.341      721015.206     1684297.174      721299.928
     1684356.202      721529.095     1684349.258      721845.067
#Sta/Elev= 30
       0 1019.01     9.5 1018.49    57.1 1016.75    95.2 1015.03   190.3 1009.89
   209.4 1009.15   266.4 1007.65     276 1007.26   285.5 1006.46     295 1003.23
   304.4  997.04   313.9  989.97   323.4  982.29   342.3  965.98   351.7  957.47
   361.2  947.83   370.7  938.83   379.5  934.17   380.1  933.85   389.6  933.27
   408.5   935.3   436.9  937.35   493.7  941.01   560.4  945.88   589.2  948.28
   598.8  949.26   637.1     954   665.8  956.97   704.1  961.79   838.2  977.76
#Mann= 3 , 0 , 0
       0      .1       0   379.5    .045       0   408.5      .1       0
Bank Sta=379.5,408.5
XS Rating Curve= 0 ,0
Exp/Cntr=0.3,0.1

Type RM Length L Ch R = 1 ,24351.6 ,22307.3,488.5,22252.7
XS GIS Cut Line= 2
     1683967.313      721362.428     1684088.841      721775.623
#Sta/Elev= 30
       0  971.71     9.8  971.43    19.6  970.68    39.2  968.74    78.3  963.94
    88.1  961.72    97.9  957.44   107.7  951.21   117.5  943.16   127.2  935.75
     137  932.36   137.7  932.35   146.8  932.16   156.6  932.77   166.4  933.28
   205.6  934.75   234.9  936.18   244.7   936.8   283.9  939.84   293.7   941.1
   303.4   943.6   313.2  946.87     323  950.38   352.4  961.27   362.2  964.46
   381.8  970.32   391.5  973.03   401.3  975.36   411.1  977.37   430.7  980.81
#Mann= 3 , 0 , 0
       0      .1       0   137.7    .045       0   156.6      .1       0
Bank Sta=137.7,156.6
XS Rating Curve= 0 ,0
Exp/Cntr=0.3,0.1

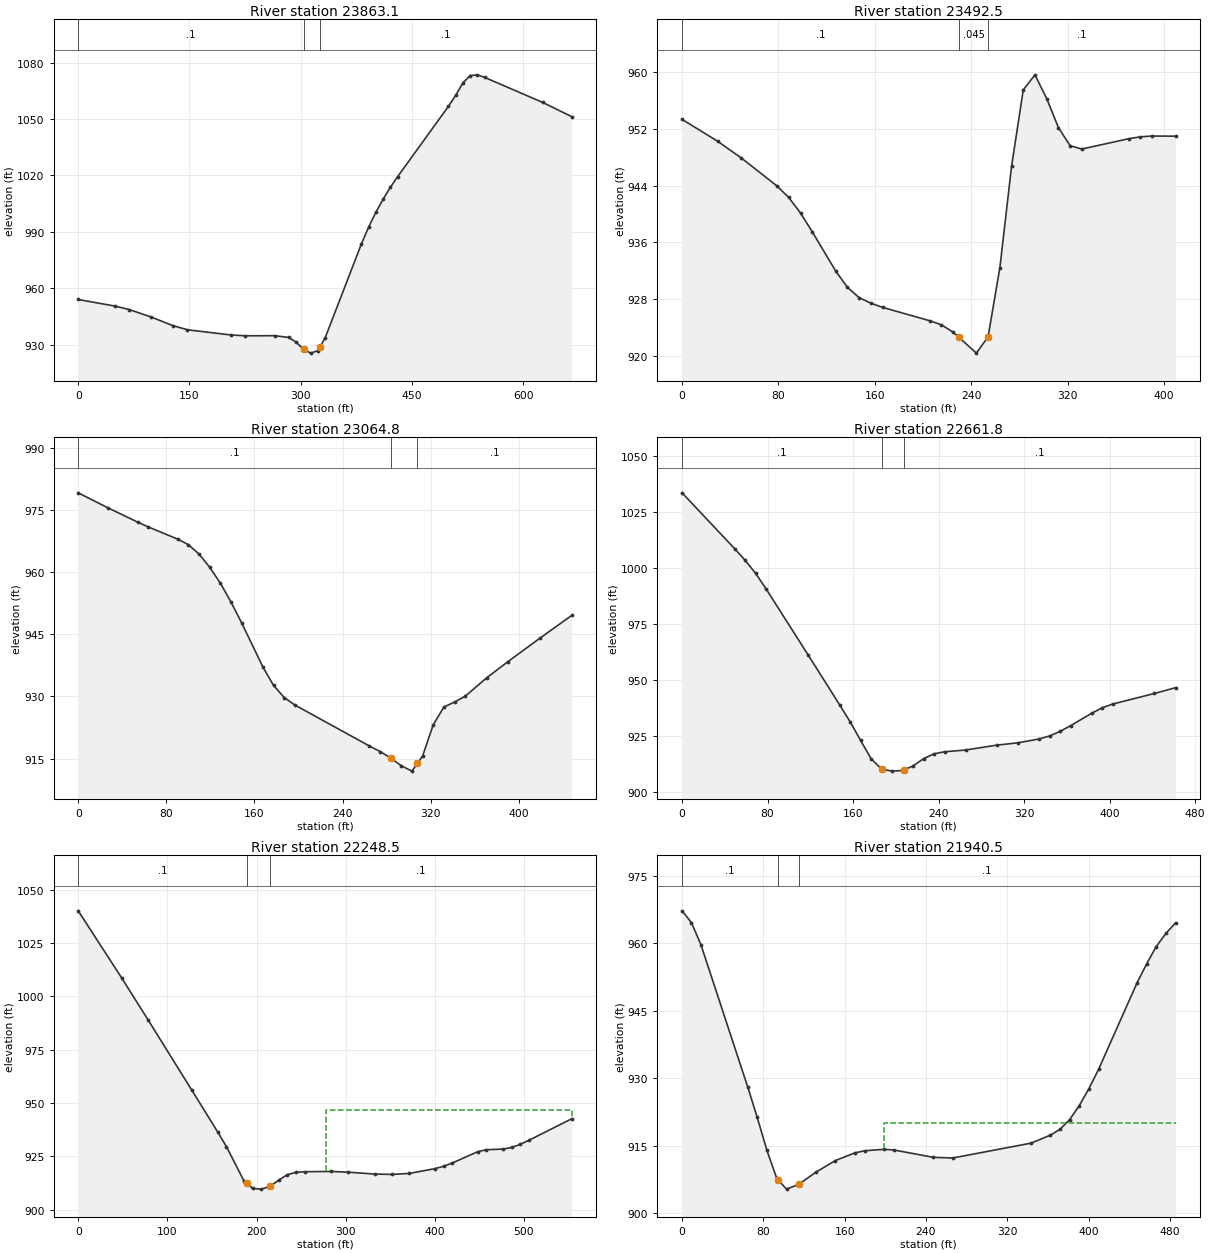
Type RM Length L Ch R = 1 ,23863.1 ,22307.3,370.6,22252.7
XS GIS Cut Line= 3
     1683786.758      721376.317     1683699.952      721470.067
     1683286.758      721813.817
#Sta/Elev= 30
       0  953.95    49.1  950.48    68.8  948.61    98.3  944.62   127.8  940.03
   147.3  937.84     206  935.07   225.5  934.64   264.6   934.7   284.1  933.75
   293.9  931.17   303.7  927.52   313.4  925.42   323.2  926.74   326.1  928.79
     333  933.68   381.8  983.56   391.6  992.54   401.4 1000.48   411.2 1007.42
   420.9 1013.72   430.7 1019.36   499.1 1056.73   508.9 1062.56   518.7 1069.24
   528.4 1073.06   538.2 1073.47     548 1072.08   626.2 1058.77   665.2 1051.24
#Mann= 3 , 0 , 0
       0      .1       0   303.7    .045       0   326.1      .1       0
Bank Sta=303.7,326.1
XS Rating Curve= 0 ,0
Exp/Cntr=0.3,0.1

Type RM Length L Ch R = 1 ,23492.5 ,22307.3,427.7,22252.7
XS GIS Cut Line= 3
     1683752.035      721272.151     1683644.396      721261.734
      1683352.73      721185.345
#Sta/Elev= 30
       0  953.33    29.5  950.26    49.2  947.89    78.6  943.98    88.5  942.34
    98.3  940.15   108.1  937.49   127.6  931.95   137.3  929.67     147  928.22
   156.8  927.44   166.5  926.85   205.4  924.98   215.1  924.41   224.8  923.39
   229.8  922.63   244.3  920.41     254  922.71   263.8  932.46   273.5  946.73
   283.2  957.48   292.9  959.61   302.7  956.25   312.4  952.18   322.1  949.62
   331.8  949.16   370.7  950.61   380.5  950.88   390.2  950.99   409.6  950.97
#Mann= 3 , 0 , 0
       0      .1       0   229.8    .045       0     254      .1       0
Bank Sta=229.8,254
XS Rating Curve= 0 ,0
Exp/Cntr=0.3,0.1

Type RM Length L Ch R = 1 ,23064.8 ,22307.3,403,22252.7
XS GIS Cut Line= 3
     1683887.452      720952.706     1683793.702      720917.984
     1683488.146      720751.317
#Sta/Elev= 30
       0   979.1    27.3  975.44    54.5  971.97    63.6  970.88    90.9  967.87
     100  966.61   109.6  964.36   119.3  961.17     129  957.34   138.6  952.83
   148.3  947.78   167.6  937.15   177.3  932.67     187  929.75   196.7  927.94
   264.3  918.07     274  916.73   283.7  915.18   293.3   913.3     303     912
     308  913.88   312.7  915.65   322.3  923.17     332  927.45   341.7  928.67
   351.4  930.07   370.7  934.47     390  938.37     419  944.02     448  949.53
#Mann= 3 , 0 , 0
       0      .1       0   283.7    .045       0     308      .1       0
Bank Sta=283.7,308
XS Rating Curve= 0 ,0
Exp/Cntr=0.3,0.1

Type RM Length L Ch R = 1 ,22661.8 ,58.9,413.2,57.4
XS GIS Cut Line= 2
     1683873.563      720348.539     1683470.785      720574.234
#Sta/Elev= 30
       0 1033.46    49.1  1008.6    58.9 1003.45    68.8  997.57    78.6  990.64
   117.9  961.22   147.4  938.96   157.2  931.43     167  923.13   176.8  914.97
   186.6   910.3   196.5   909.4   206.3  909.68   207.6  909.95   216.1  911.71
   225.9  914.94   235.8  917.13   245.6  918.02   265.2  918.81   294.7     921
   314.4  922.03     334  923.74   343.8  925.07   353.6   927.1   363.5  929.66
   383.1  935.16   392.9   937.6   402.8  939.29     442  944.03   461.7   946.6
#Mann= 3 , 0 , 0
       0      .1       0   186.6    .045       0   207.6      .1       0
Bank Sta=186.6,207.6
XS Rating Curve= 0 ,0
Exp/Cntr=0.3,0.1

Type RM Length L Ch R = 1 ,22248.5 ,327.7,308,287.9
XS GIS Cut Line= 3
     1683639.682      719962.868     1683360.199      720207.539
     1683339.251      720388.367
#Sta/Elev= 30
       0 1040.15    48.9 1008.57    78.2   989.1   127.1  956.22   156.4  936.42
   166.2  929.56   185.7  913.61   189.3  912.25   195.5  909.91   205.3  909.58
     215  910.82   224.8  913.76   234.6  916.38   244.4  917.47   254.2  917.74
   283.5  917.88     303  917.53   332.4  916.65   351.9  916.48   371.4  916.95
   400.2  919.19   409.8  920.31   419.4  921.79   448.1  927.13   457.7  928.07
   476.8  928.38   486.4  929.15     496  930.64   505.6  932.51   553.5  942.58
#Mann= 3 , 0 , 0
       0      .1       0   189.3    .045       0     215      .1       0
#XS Ineff= 2 , 0
                          277.95          946.79
Permanent Ineff=
       F       F
Bank Sta=189.3,215
XS Rating Curve= 0 ,0
Exp/Cntr=0.3,0.1

Type RM Length L Ch R = 1 ,21940.5 ,328.7,350.9,369.8
XS GIS Cut Line= 4
     1683238.381      719872.441     1683213.381      719941.978
     1683220.345       720211.46     1683144.577      720331.723
#Sta/Elev= 30
       0  967.26     9.2  964.64    18.5  959.75    64.7  927.99    73.9  921.32
    83.5  913.94    93.2  907.69    94.3 907.418   102.8  905.32   114.8 906.375
   131.7  909.09   150.9  911.69   170.2   913.4   179.8  913.86     199  914.19
   208.7  914.02   247.2   912.4   266.4  912.25   343.5  915.56   362.4  917.33
   371.9  918.63   381.4   920.8   390.8  923.88   400.3  927.66   409.8  931.95
   447.7  951.22   457.2  955.46   466.6  959.31   476.1  962.23   485.6  964.58
#Mann= 3 , 0 , 0
       0      .1       0    94.3    .045       0   114.8      .1       0
#XS Ineff= 2 , 0
       0                     199       0     920
Permanent Ineff=
       F       F
Bank Sta=94.3,114.8
XS Rating Curve= 0 ,0
Exp/Cntr=0.3,0.1

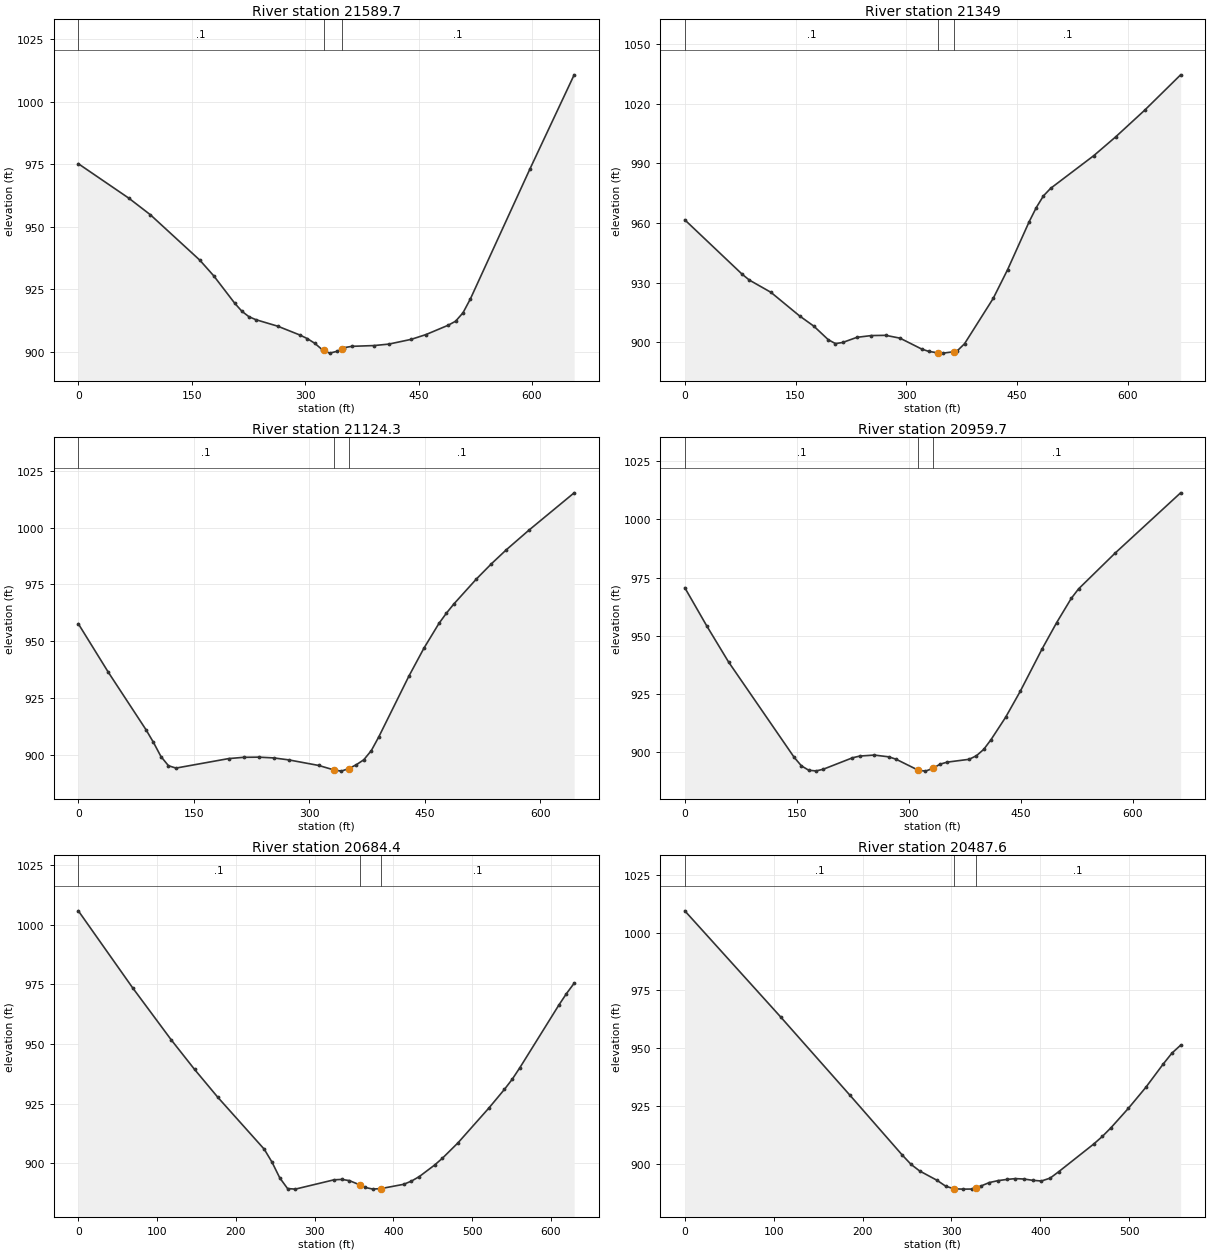
Type RM Length L Ch R = 1 ,21589.7 ,232,240.7,248.8
XS GIS Cut Line= 4
     1683267.358      719823.364     1683162.563      719825.064
     1683027.826      719789.453     1682719.465      720062.188
#Sta/Elev= 30
       0  975.24    66.7  961.46    95.3   954.8   160.6  936.65   179.1  930.35
     207  919.32   216.3  916.18   225.6  913.99   234.9  912.78   263.8  910.18
   293.2  906.63     303  905.19   312.8  903.32   322.6  900.78   324.9  900.46
   332.4   899.4   342.2  900.13   348.9901.1418     352  901.61   361.8  902.12
   391.2  902.43   410.8  903.02   440.2  904.91   459.8  906.83   489.2  910.57
     499  912.18   508.8  915.56   518.6  921.15     597  972.94   655.8 1010.83
#Mann= 3 , 0 , 0
       0      .1       0   324.9    .045       0   348.9      .1       0
Bank Sta=324.9,348.9
XS Rating Curve= 0 ,0
Exp/Cntr=0.3,0.1

Type RM Length L Ch R = 1 ,21349   ,230.7,224.7,218
XS GIS Cut Line= 3
     1683152.848       719537.34     1682669.615      719715.503
     1682548.399      719814.787
#Sta/Elev= 30
       0  961.63    77.7   934.3    87.5  931.34   116.6  925.22   155.5  913.33
   174.9  908.16   194.4  901.36   204.1  899.42   213.8  899.98   233.2  902.57
   252.7  903.46   272.1  903.58   291.5  902.16   320.7  896.72   330.4   895.5
   342.8  894.79   349.8  894.63   364.8895.3489   369.3  895.85     379  899.36
   417.8  922.14   437.3  936.59   466.4   960.6   476.2  967.83   485.9   973.7
   495.6  977.47   554.2  993.95   583.6 1003.31   622.8 1016.68   671.7 1034.53
#Mann= 3 , 0 , 0
       0      .1       0   342.8    .045       0   364.8      .1       0
Bank Sta=342.8,364.8
XS Rating Curve= 0 ,0
Exp/Cntr=0.3,0.1

Type RM Length L Ch R = 1 ,21124.3 ,167.2,164.6,161.3
XS GIS Cut Line= 2
     1682985.577       719269.69     1682465.233      719649.236
#Sta/Elev= 30
       0   957.7      39  936.36    87.8  911.17    97.6  905.55   107.3  899.34
   117.1  895.28   126.9  894.25   195.2  898.42   214.7  898.98   234.2  899.06
   253.7  898.72   273.2  897.86   312.3   895.4   331.8  893.46   341.6  892.91
   351.3  894.02   361.1  895.72   370.8  897.89   380.6  901.94   390.3  907.97
   429.4  934.67   448.9  946.94   468.4  957.82   478.2  962.38   487.9  966.43
   517.2  977.42   536.7   984.1   556.2   990.3   585.5   998.9   644.1 1015.27
#Mann= 3 , 0 , 0
       0      .1       0   331.8    .045       0   351.3      .1       0
Bank Sta=331.8,351.3
XS Rating Curve= 0 ,0
Exp/Cntr=0.3,0.1

Type RM Length L Ch R = 1 ,20959.7 ,279,275.3,269.8
XS GIS Cut Line= 2
     1682871.371      719104.256     1682389.474      719561.569
#Sta/Elev= 30
       0  970.64    29.3  954.28    58.6  938.74   146.6  897.71   156.3  894.06
   166.1  892.18   175.9  891.88   185.6  892.62   224.7  897.53   234.5  898.28
     254   898.7   273.6  897.93   283.3  896.89   312.6  892.23   322.4   891.8
   332.2  892.93   341.9  894.77   351.7  895.67     381  896.88   390.8  898.42
   400.6  901.16   410.3  905.32   429.9  914.95   449.4  926.05   478.7  944.29
   498.3  955.64   517.8  966.02   527.6  970.12   576.4  985.44   664.4 1011.42
#Mann= 3 , 0 , 0
       0      .1       0   312.6    .045       0   332.2      .1       0
Bank Sta=312.6,332.2
XS Rating Curve= 0 ,0
Exp/Cntr=0.3,0.1

Type RM Length L Ch R = 1 ,20684.4 ,188.8,196.8,205.3
XS GIS Cut Line= 2
     1682683.375      718848.185     1682293.317      719342.208
#Sta/Elev= 30
       0 1005.85    68.8  973.61     118  951.68   147.5  939.33     177  927.64
     236  905.83   245.9  900.37   255.7   893.8   265.6  889.32   275.4  889.08
   324.6  892.99   334.4  893.16   344.2  892.64   357.1890.8794   363.9  889.79
   373.7  889.11   384.1889.3011   413.1  891.11   422.9  892.46   432.8  894.34
   452.4  899.22   462.2  902.06   481.9  908.49   521.3  923.16   540.9  930.94
   550.8  935.19   560.6   940.1   609.8  966.22   619.6   971.1   629.4  975.48
#Mann= 3 , 0 , 0
       0      .1       0   357.1    .045       0   384.1      .1       0
Bank Sta=357.1,384.1
XS Rating Curve= 0 ,0
Exp/Cntr=0.3,0.1

Type RM Length L Ch R = 1 ,20487.6 ,329.1,314,298.5
XS GIS Cut Line= 2
     1682615.817      718791.468     1682155.541      719106.688
#Sta/Elev= 30
       0 1009.42   107.7  963.57     186  929.55   244.7  903.74   254.5  899.74
   264.2  896.87   283.8  892.82   293.6  890.26   303.1889.1259   313.2     889
     323  889.04   327.1  889.56   332.8  890.28   342.6  891.84   352.3  892.66
   362.1  893.18   371.9  893.55   381.7  893.37   391.5  892.81   401.3  892.52
   411.1  893.77   420.8  896.56     460  908.48   469.8  911.79   479.6  915.59
   499.2     924   518.7  933.02   538.3  943.13   548.1  947.84   557.9  951.28
#Mann= 3 , 0 , 0
       0      .1       0   303.1    .045       0   327.1      .1       0
Bank Sta=303.1,327.1
XS Rating Curve= 0 ,0
Exp/Cntr=0.3,0.1

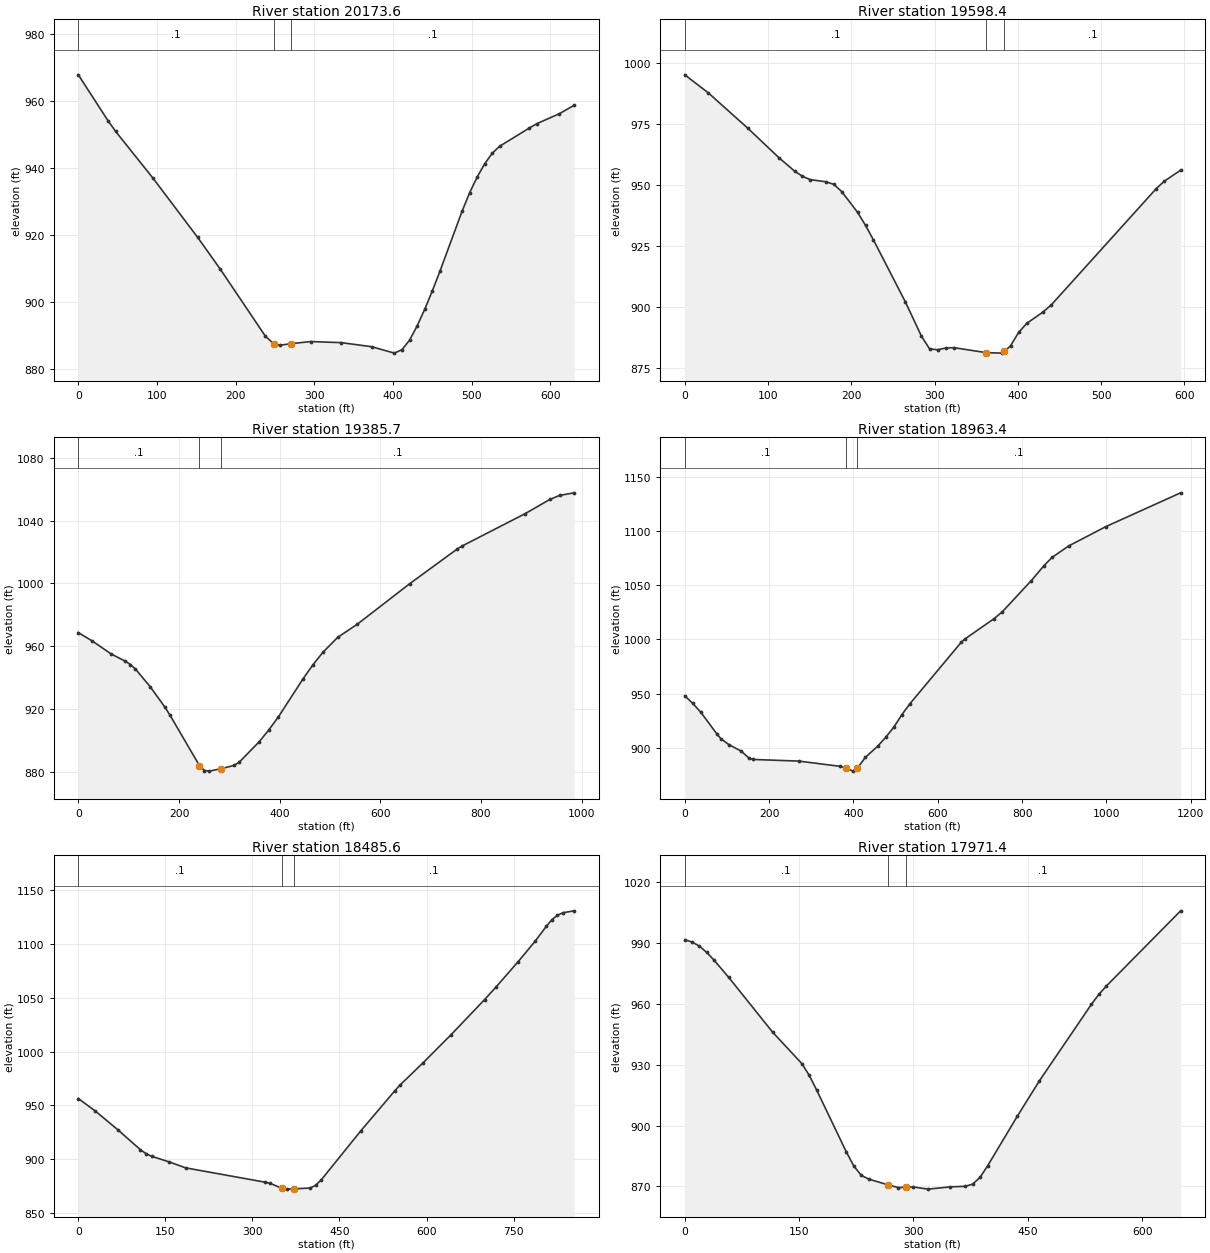
Type RM Length L Ch R = 1 ,20173.6 ,599.1,575.2,547.2
XS GIS Cut Line= 4
     1682276.553      718528.247     1682158.982      718712.128
     1682092.503      718924.424     1682089.053      719114.184
#Sta/Elev= 30
       0  967.76      38  953.98    47.4   950.9    94.9  936.96   151.8  919.28
   180.3   909.9   237.6  889.93   248.3  887.58   256.9  887.15     270887.5967
   295.6  888.24   334.3  887.92     373   886.7     402  884.79   411.7  885.85
   421.4  888.72     431  892.98   440.7  897.98   450.2  903.39   459.7  909.13
   488.2  927.23   497.6  932.59   507.1  937.25   516.6  941.19   526.1  944.32
   535.6  946.44   573.6  951.92   583.1   953.2   611.5  956.15   630.5  958.68
#Mann= 3 , 0 , 0
       0      .1       0   248.3    .045       0     270      .1       0
Bank Sta=248.3,270
XS Rating Curve= 0 ,0
Exp/Cntr=0.3,0.1

Type RM Length L Ch R = 1 ,19598.4 ,211.9,212.7,213.9
XS GIS Cut Line= 4
     1681656.554      718693.006     1681683.637      718860.367
     1681735.166      718928.634      1681973.73      719171.688
#Sta/Elev= 30
       0  995.13    28.3  987.73    75.4  973.36     113  961.22   131.9  955.71
   141.3   953.6   150.7  952.23   169.5  951.35     179   950.3   188.6  947.29
   207.6  938.82   217.1  933.49   226.6  927.56   264.8  902.28   284.3  888.13
     294  882.97   303.7  882.57   313.4  883.28   323.2  883.44   362.1   881.4
   381.6   881.2   383.9  881.92   391.3  884.22     401  889.65   410.8  893.39
   430.2     898     440  900.86   566.4  948.58   576.2  951.64   595.6   956.1
#Mann= 3 , 0 , 0
       0      .1       0   362.1    .045       0   383.9      .1       0
Bank Sta=362.1,383.9
XS Rating Curve= 0 ,0
Exp/Cntr=0.3,0.1

Type RM Length L Ch R = 1 ,19385.7 ,408.4,422.3,435.7
XS GIS Cut Line= 5
     1681486.134      718897.892     1681541.741      718960.639
     1681860.426       719320.24     1682013.268      719445.719
     1682116.204      719643.398
#Sta/Elev= 30
       0   968.7      28  963.29    65.2   955.1    93.6  950.43   103.4  948.36
   113.3  945.55   142.7  934.26   172.1  921.16   181.9  916.19   240.7   883.9
   250.5  880.84   260.4  880.44   284.1882.0145   309.4   884.1   319.2  886.01
   358.4  898.85     378  906.51   397.6  915.08   446.7  939.38   466.3  948.29
   485.9  956.15   515.3  965.69   554.5  974.11   658.5  999.91   752.7 1021.97
   762.1 1023.83   888.1 1044.57   936.5 1053.51   955.9  1056.1     985 1057.76
#Mann= 3 , 0 , 0
       0      .1       0   240.7    .045       0   284.1      .1       0
Bank Sta=240.7,284.1
XS Rating Curve= 0 ,0
Exp/Cntr=0.3,0.1

Type RM Length L Ch R = 1 ,18963.4 ,446.1,477.8,509
XS GIS Cut Line= 5
     1681393.982      718935.065     1681288.633      719045.891
     1681329.845      719377.296     1681234.259      719527.079
     1680843.634       719856.94
#Sta/Elev= 30
       0  948.03    19.1  940.98    38.2  932.83    76.4  912.74      86  908.35
   105.1  902.96   133.8  897.04   152.9  890.38   162.7  889.39   270.8  887.88
     369     883     383881.5443   398.5  878.64   409.4881.3682   427.9  891.26
   457.4  901.61     477  910.04   496.2  919.46   514.9  930.75   533.6  940.63
   655.2  997.26   664.6 1000.52   733.4 1019.18     753 1025.52   821.9 1054.31
   851.4 1067.87     871 1075.65   910.4  1086.2   998.8 1104.07  1175.8 1135.15
#Mann= 3 , 0 , 0
       0      .1       0     383    .045       0   409.4      .1       0
Bank Sta=383,409.4
XS Rating Curve= 0 ,0
Exp/Cntr=0.3,0.1

Type RM Length L Ch R = 1 ,18485.6 ,502.8,514.2,526.5
XS GIS Cut Line= 3
     1681380.224      718875.677     1680815.355      719058.673
     1680557.435      719096.353
#Sta/Elev= 30
       0  956.43    29.2  944.87    68.1  927.44   107.1  908.86   116.8  905.28
   126.5  902.77   155.7  897.76     185  892.06   321.2  878.83     331  877.58
   350.4  873.14   360.2  872.32   371.3  872.59   399.1  873.32   408.8   875.8
   418.6  880.95   486.7  926.43   545.1   963.5   554.8  969.24   593.8  989.52
     642 1015.55     700  1048.3   719.3 1059.74   757.9 1083.58   786.8 1102.29
   806.2 1116.23   815.8 1122.39   825.5 1126.71   835.1    1129   854.4 1130.77
#Mann= 3 , 0 , 0
       0      .1       0   350.4    .045       0   371.3      .1       0
Bank Sta=350.4,371.3
XS Rating Curve= 0 ,0
Exp/Cntr=0.3,0.1

Type RM Length L Ch R = 1 ,17971.4 ,338.8,340.1,337.7
XS GIS Cut Line= 3
      1681435.84      718599.545     1681293.005      718616.962
     1680788.208      718573.375
#Sta/Elev= 30
       0  991.58     9.6  990.44    19.2  988.44    28.8  985.32    38.4  981.53
    57.6  973.06   115.1  946.11   153.6  930.56   163.4   924.7   173.1  917.48
   212.1  886.91   221.8  880.07   231.6  875.48   241.3  873.64     266  870.88
   280.3  869.46     290  869.67   299.8  869.76   319.3   868.7   348.5  869.82
     368   870.1   377.7  871.15   387.5  874.55   397.2  880.09   436.2  904.56
   465.4  922.13   533.6   959.8   543.4  964.71   553.1  968.77   650.6 1005.84
#Mann= 3 , 0 , 0
       0      .1       0     266    .045       0     290      .1       0
Bank Sta=266,290
XS Rating Curve= 0 ,0
Exp/Cntr=0.3,0.1

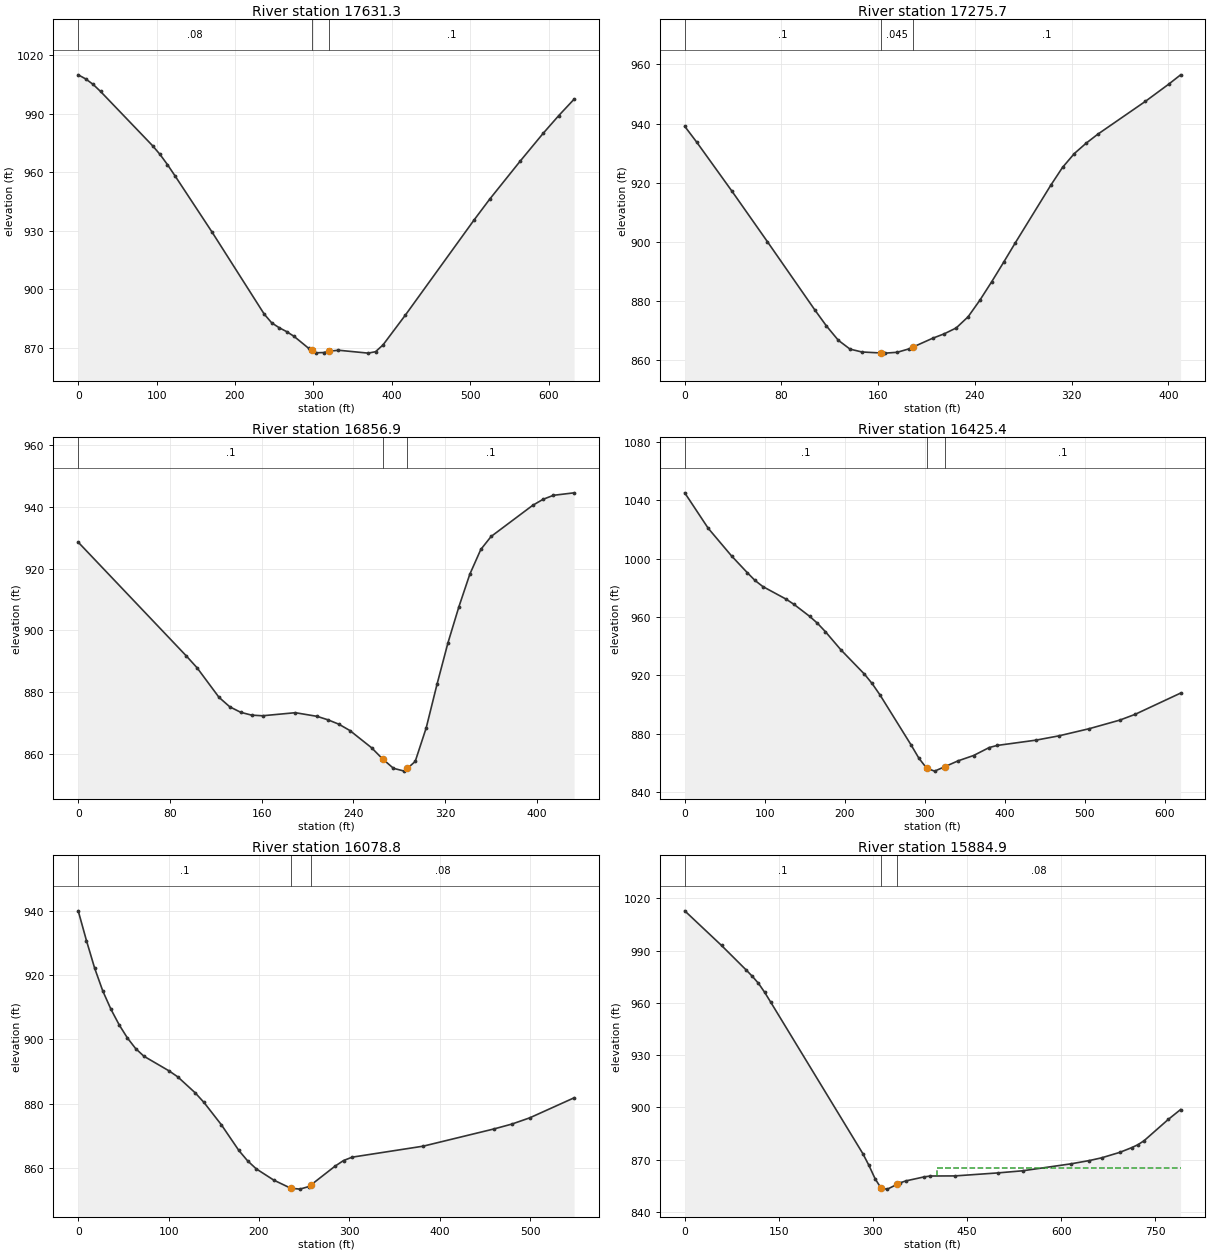
Type RM Length L Ch R = 1 ,17631.3 ,360.2,355.7,351.6
XS GIS Cut Line= 4
     1681489.861      718338.915     1681243.585      718322.417
     1681070.793      718272.651     1680864.861      718267.734
#Sta/Elev= 30
       0 1010.03     9.5 1007.94      19 1005.13    28.5  1001.5    94.9  973.66
   104.4  969.18   113.9  963.95   123.4  958.28   170.9  929.27   237.3  887.29
   246.8  882.83   256.3  880.33   265.8  878.33   275.2  875.93   294.2  869.68
   297.7  868.85   303.6  867.46   313.1  867.58   319.7868.2119     332  868.77
   369.9  867.28   379.3  868.01   388.8  871.47   417.2   886.7   505.1  935.63
   524.7  946.13     564  965.85   593.4  980.14     613  989.11   632.6  997.53
#Mann= 3 , 0 , 0
       0     .08       0   297.7    .045       0   319.7      .1       0
Bank Sta=297.7,319.7
XS Rating Curve= 0 ,0
Exp/Cntr=0.3,0.1

Type RM Length L Ch R = 1 ,17275.7 ,404,418.7,432.6
XS GIS Cut Line= 2
      1681349.59      717981.348     1680939.442      717983.774
#Sta/Elev= 30
       0  939.05     9.8  933.76    39.1  917.11    68.4  900.06   107.4  877.13
   117.2   871.6     127  866.77   136.7  863.77   146.5   862.8   162.2862.4594
     166  862.41   175.8   862.7   185.6  863.86   188.7864.4417   205.1  867.44
   214.8  868.96   224.6  870.93   234.4  874.69   244.1  880.27   253.9  886.52
   263.7  893.05   273.4  899.65   302.7  919.08   312.5  925.16   322.3  929.86
     332  933.33   341.8  936.42   380.9  947.44   400.4  953.31   410.2  956.45
#Mann= 3 , 0 , 0
       0      .1       0   162.2    .045       0   188.7      .1       0
Bank Sta=162.2,188.7
XS Rating Curve= 0 ,0
Exp/Cntr=0.3,0.1

Type RM Length L Ch R = 1 ,16856.9 ,453.4,431.6,408.7
XS GIS Cut Line= 4
     1681428.752      717696.013     1681334.846      717703.678
     1681124.529      717556.092     1681044.203      717569.277
#Sta/Elev= 30
       0  928.57    94.2  891.72   103.7  887.83   122.8  878.26   132.3  875.15
   141.8  873.39   151.3  872.47   160.8  872.27   189.4  873.26   208.4  872.08
   217.9  870.95   227.4  869.53     237  867.48     256  861.87   265.5  858.28
     275  855.23   284.5  854.31   287.1  855.17     294  857.46   303.6  868.36
   313.1   882.6   322.6  895.98   332.1  907.62   341.6  918.15   351.2   926.2
   360.2  930.42   396.4   940.5   405.4  942.45   414.5  943.77   432.6  944.58
#Mann= 3 , 0 , 0
       0      .1       0   265.5    .045       0   287.1      .1       0
Bank Sta=265.5,287.1
XS Rating Curve= 0 ,0
Exp/Cntr=0.3,0.1

Type RM Length L Ch R = 1 ,16425.4 ,356,346.6,336.4
XS GIS Cut Line= 3
     1681661.276      717115.686     1681251.295      717272.581
     1681106.148      717379.995
#Sta/Elev= 30
       0 1045.25    29.3 1020.94    58.5 1001.94      78  990.55    87.8  985.12
    97.6  980.92   126.8  972.24   136.6  968.66   156.1  960.47   165.8  955.75
   175.6  950.06   195.1  937.51   224.4   920.9   234.1  914.39   243.9   906.6
   282.9  872.14   292.6  863.08   302.4   856.2   312.2  854.25   324.9857.2719
   341.4  861.28   360.9  864.97   380.4  870.43   390.2  871.86     439  875.52
   467.5  878.46   505.5  883.39   543.5  889.25   562.5  893.17   619.6  907.81
#Mann= 3 , 0 , 0
       0      .1       0   302.4    .045       0   324.9      .1       0
Bank Sta=302.4,324.9
XS Rating Curve= 0 ,0
Exp/Cntr=0.3,0.1

Type RM Length L Ch R = 1 ,16078.8 ,195.6,193.9,192.1
XS GIS Cut Line= 4
     1681310.349      716734.401     1681296.895      716824.233
     1681142.434      716983.586      1681086.39        717212.7
#Sta/Elev= 30
       0  939.96     9.1  930.74    18.2  922.14    27.2  915.06    36.3  909.34
    45.4  904.51    54.5  900.44    63.6  897.16    72.7   894.8   100.5  890.25
   110.1   888.4   129.4  883.44   139.1  880.46   158.4   873.5   177.7  865.54
   187.3  862.34     197  859.81   216.3  856.33   234.9853.8287   245.2  853.52
   254.9   854.3   257.9854.9063   283.8  860.58   293.5   862.4   303.1  863.45
   381.6  866.86   460.2  872.23   479.8  873.73   499.5  875.66   548.6  881.88
#Mann= 3 , 0 , 0
       0      .1       0   234.9    .045       0   257.9     .08       0
Bank Sta=234.9,257.9
XS Rating Curve= 0 ,0
Exp/Cntr=0.3,0.1

Type RM Length L Ch R = 1 ,15884.9 ,167.5,149.2,133.1
XS GIS Cut Line= 3
      1681250.22      716558.298     1680907.871       716973.78
     1680920.023      717225.516
#Sta/Elev= 30
       0 1012.91    58.7  992.99    97.9  978.93   107.7   975.3   117.5  971.26
   127.2   966.2     137  960.46   283.9   873.4   293.6  866.65   303.4  858.99
   313.2  853.46   313.6853.4421     323  853.02   339.1855.8615   342.6  856.54
   352.4  857.74   381.7  860.06   391.5  860.56   430.7  860.61   499.2  862.34
   538.4  863.55   615.9  867.57     645  869.44   664.4     871   693.4  874.14
   712.8  876.91   722.5  878.57   732.2  880.85     771  893.16   790.4  898.76
#Mann= 3 , 0 , 0
       0      .1       0   313.6    .045       0   339.1     .08       0
#XS Ineff= 2 , 0
       0                   401.3       0     865
Permanent Ineff=
       F       F
Bank Sta=313.6,339.1
XS Rating Curve= 0 ,0
Exp/Cntr=0.3,0.1

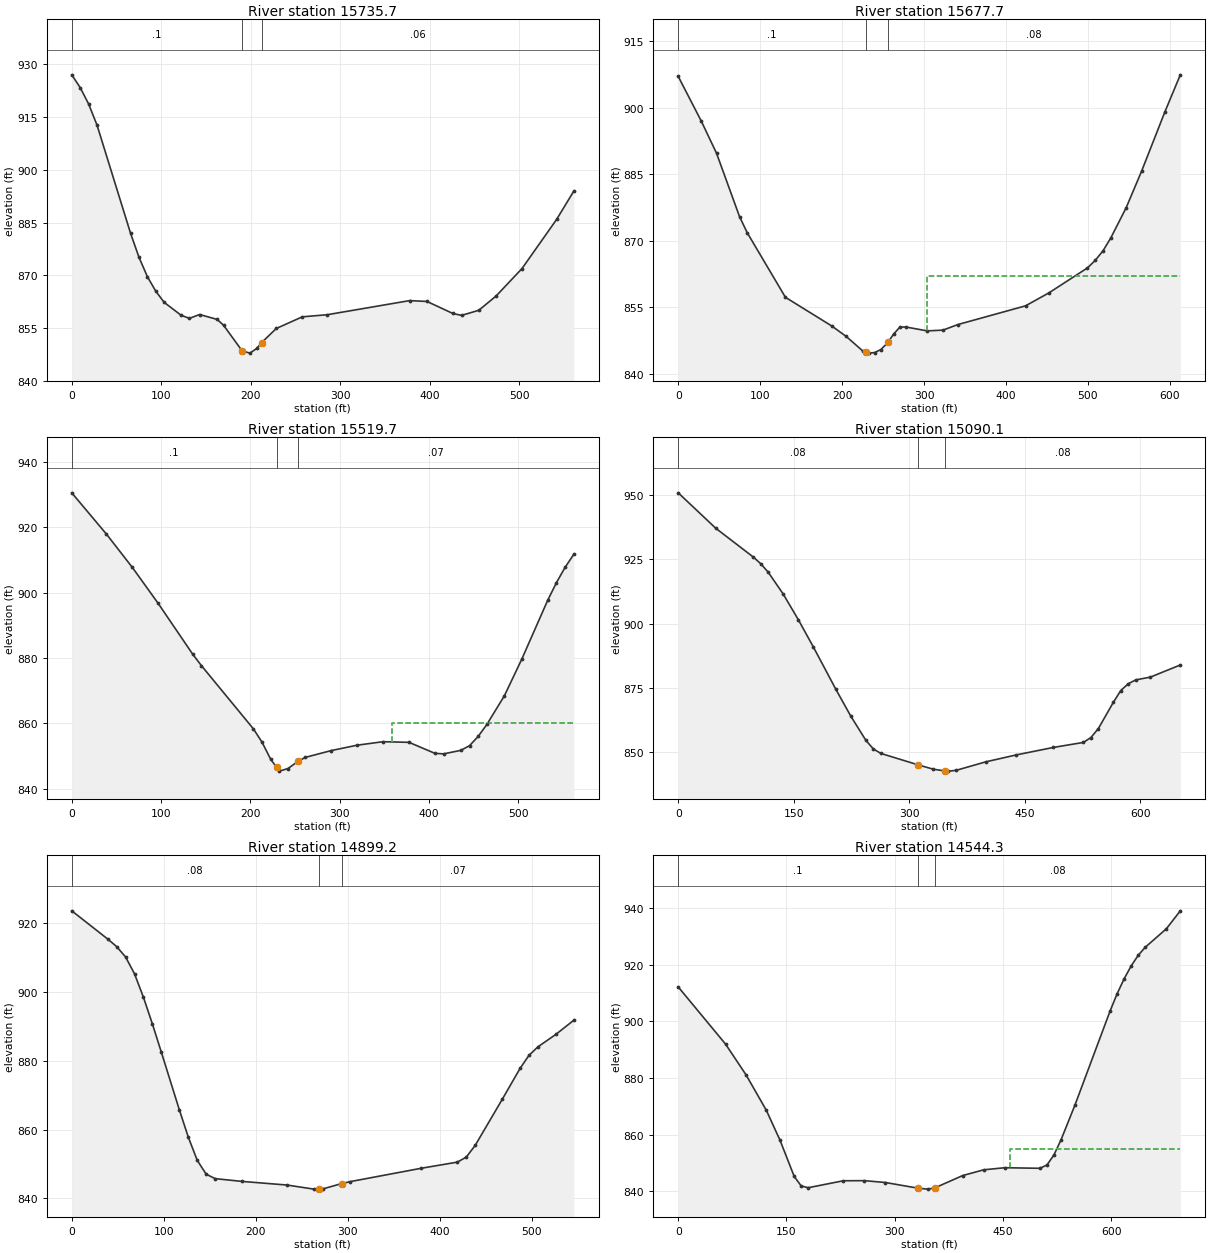
Type RM Length L Ch R = 1 ,15735.7 ,61.9,58,56.2
XS GIS Cut Line= 6
     1680917.085      716590.481      1680882.05      716717.131
     1680899.429      716734.771     1680905.724      716792.162
     1680866.425      716940.221     1680742.085      717087.704
#Sta/Elev= 30
       0  927.03     9.4   923.4    18.8  918.75    28.2  912.72    65.7  881.91
    75.1  875.09    84.5  869.56    93.9  865.43   103.2  862.28     122  858.63
   131.4  857.72   142.8  858.82   162.4  857.42   169.5  855.78   190.3  848.47
     199  847.83   206.8   849.2     212850.8148   228.4  854.84   257.5  858.16
   285.1  858.75   377.5  862.78   396.8  862.53   425.7  859.11   435.4  858.57
   454.7  860.03     474   864.1   502.9   871.9   541.5  885.86   560.8  893.96
#Mann= 3 , 0 , 0
       0      .1       0   190.3    .045       0     212     .06       0
Bank Sta=190.3,212
XS Rating Curve= 0 ,0
Exp/Cntr=0.3,0.1

Type RM Length L Ch R = 1 ,15677.7 ,143,158,168.1
XS GIS Cut Line= 6
     1680792.779       716554.37     1680780.715      716684.652
     1680842.339      716725.344     1680849.825      716803.082
     1680813.213      716937.443     1680688.613       717079.37
#Sta/Elev= 30
       0  907.04      28     897    46.7  889.72    74.8  875.41    84.1   871.8
   130.8   857.2   187.4  850.72   204.9  848.38   225.4  845.06   229.1  844.82
   232.6   844.6   239.6  844.73   247.3   845.4   256.1847.0543   262.7  848.88
   270.4  850.46   277.4  850.51   303.8  849.62   323.1  849.79   341.1  851.04
   423.8  855.27   452.2  858.18   499.4  863.83   508.8  865.52   518.3  867.67
   527.7  870.54   546.6   877.4   565.5  885.68   593.8  899.01   612.7   907.4
#Mann= 3 , 0 , 0
       0      .1       0   229.1    .045       0   256.1     .08       0
#XS Ineff= 2 , 0
       0                   303.8       0     862
Permanent Ineff=
       F       F
Bank Sta=229.1,256.1
XS Rating Curve= 0 ,0
Exp/Cntr=0.3,0.1

Type RM Length L Ch R = 1 ,15519.7 ,433.8,429.7,432.8
XS GIS Cut Line= 3
     1680789.698      716474.119     1680623.075      716907.913
     1680571.599      716990.612
#Sta/Elev= 30
       0  930.54    38.7  917.94    67.8  907.71    96.8  896.67   135.5   881.1
   145.2  877.62   203.3   858.3     213   854.2   222.7  848.98   229.4846.4653
   232.4  845.34     242  846.13   253.4848.3442   261.4  849.54   290.4  851.63
   319.5  853.28   348.5  854.35   377.6  854.15   406.6  850.78   416.3  850.63
   435.6   851.7   445.3  853.13     455  855.97   464.7  859.62   484.2  868.34
   503.7  879.55   532.9  897.68   542.6  903.03   552.4  907.77   562.1  911.74
#Mann= 3 , 0 , 0
       0      .1       0   229.4    .045       0   253.4     .07       0
#XS Ineff= 2 , 0
       0                   358.2       0     860
Permanent Ineff=
       F       F
Bank Sta=229.4,253.4
XS Rating Curve= 0 ,0
Exp/Cntr=0.3,0.1

Type RM Length L Ch R = 1 ,15090.1 ,191.1,190.9,181.5
XS GIS Cut Line= 3
     1680344.054      716265.505     1680273.421      716796.504
     1680184.019      716870.435
#Sta/Elev= 30
       0  950.88    48.7   937.1    97.4   925.9   107.1   923.3   116.9  919.96
   136.4  911.43   155.8  901.56   175.3  890.96   204.5  874.49     224  863.98
   243.5  854.61   253.2  851.24     263  849.49   311.3845.0451   331.2  843.34
   345.8842.6841   350.6   842.6   360.4  842.88   399.3  846.22   438.3  848.88
     487  851.82   525.9  853.77   535.7  855.68   545.3  859.16   564.7  869.32
   574.4  873.95     584  876.56   593.7  878.08     613   879.2   651.7   883.9
#Mann= 3 , 0 , 0
       0     .08       0   311.3    .045       0   345.8     .08       0
Bank Sta=311.3,345.8
XS Rating Curve= 0 ,0
Exp/Cntr=0.3,0.1

Type RM Length L Ch R = 1 ,14899.2 ,350.5,354.9,355.3
XS GIS Cut Line= 2
     1680157.016      716344.903     1680125.204       716889.58
#Sta/Elev= 30
       0  923.49      39  915.31    48.7  913.12    58.5  910.09    68.2  905.19
    77.9  898.38    87.7  890.58    97.4   882.4   116.9  865.72   126.7  857.73
   136.4  851.02   146.1  847.02   155.9  845.73   185.1  844.93   233.8  843.88
   263.1  842.69   268.3  842.72   272.8  842.75   293.3844.3018     302  844.84
     380  848.76     419  850.53   428.7  851.98   438.4  855.39   467.7  868.72
   487.2  877.76   496.9  881.55   506.6  884.01   526.1  887.62   545.6  891.74
#Mann= 3 , 0 , 0
       0     .08       0   268.3    .045       0   293.3     .07       0
Bank Sta=268.3,293.3
XS Rating Curve= 0 ,0
Exp/Cntr=0.3,0.1

Type RM Length L Ch R = 1 ,14544.3 ,484.2,501.8,516.6
XS GIS Cut Line= 3
     1679932.717      716311.841      1679870.94      716427.887
     1679748.511      716978.808
#Sta/Elev= 30
       0  912.14    65.7  891.93    93.9  881.16   122.1  868.62   141.2  857.97
   160.7   845.3   170.4  841.93   180.1  841.31   228.8  843.76     258   843.8
   287.2  843.14   332.3 841.146   345.5  840.81   355.3  841.21   394.2   845.6
   423.4  847.63   452.6  848.36   501.2  848.16     511  849.33   520.7  852.89
   530.4  858.14   549.9  870.54   598.5  903.67   608.2  909.72     618  915.05
   627.7  919.54   637.4  923.28   647.2  926.14   676.4  932.64   695.8  938.99
#Mann= 3 , 0 , 0
       0      .1       0   332.3    .045       0   355.3     .08       0
#XS Ineff= 2 , 0
       0                     460       0     855
Permanent Ineff=
       F       F
Bank Sta=332.3,355.3
XS Rating Curve= 0 ,0
Exp/Cntr=0.3,0.1