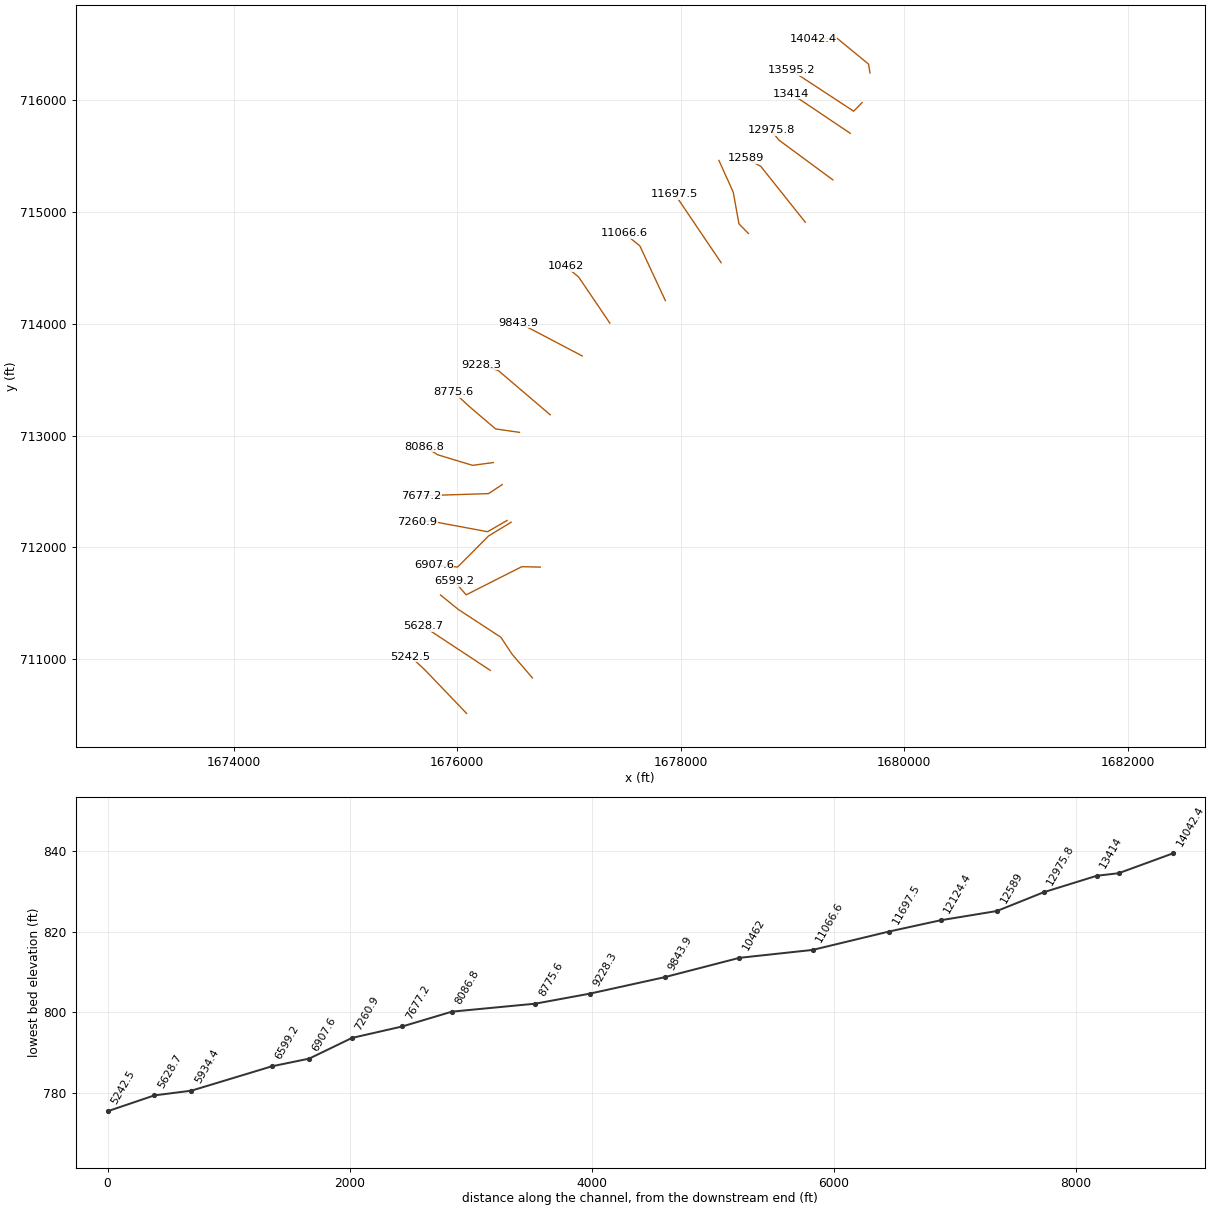
HEC-RAS study NFKINGSCK.prj: NFKINGSCK

--- NFKINGSCK.g01 (geometry) --- (continued)

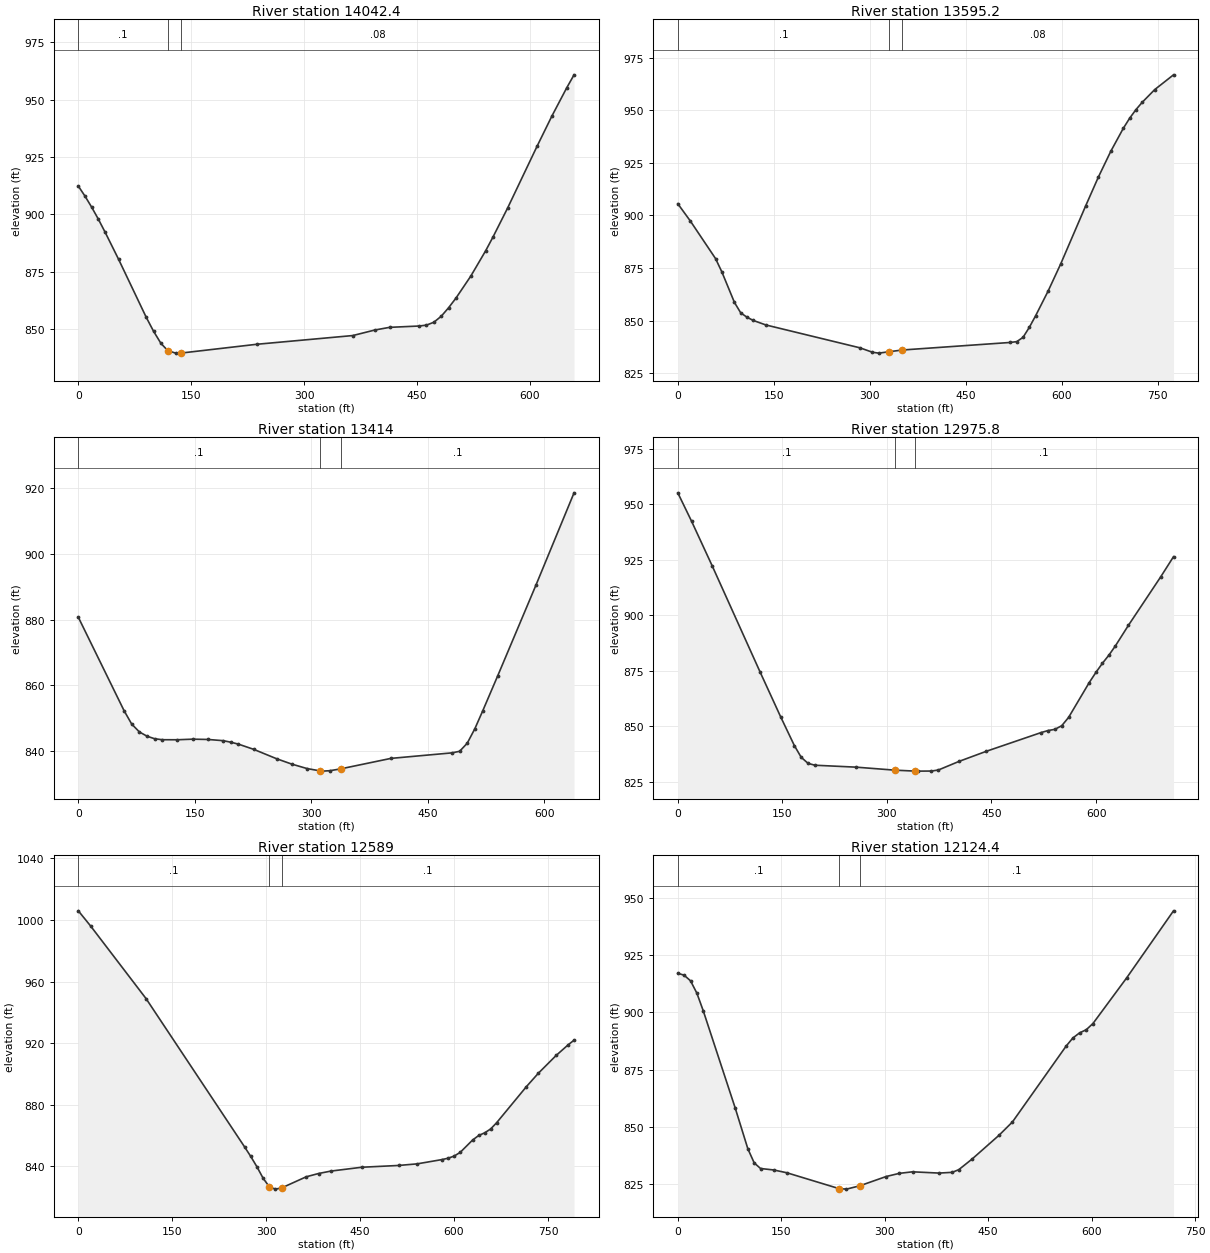
Type RM Length L Ch R = 1 ,14042.4 ,444.8,447.2,449.3
XS GIS Cut Line= 4
     1679693.394      716242.397     1679680.233      716321.653
     1679399.905      716551.942      1679184.28      716549.689
#Sta/Elev= 30
       0  912.28     8.9  907.88    17.8  903.05    26.8  897.74    35.7  892.11
    53.6   880.3    90.2   855.1     100  848.98   109.8   843.7   118.9840.5428
   129.4  839.45   136.9  839.49   237.2  843.31   364.7  847.11   394.1  849.53
   413.7  850.69   452.9  851.27   462.7  851.66   472.5  852.92   482.3  855.53
   492.1  859.24   501.9  863.46   521.6  873.04   541.2     884     551  890.02
   570.6  902.77   609.8  929.75   629.4  942.84     649  955.08   658.8  960.79
#Mann= 3 , 0 , 0
       0      .1       0   118.9    .045       0   136.9     .08       0
Bank Sta=118.9,136.9
XS Rating Curve= 0 ,0
Exp/Cntr=0.3,0.1

Type RM Length L Ch R = 1 ,13595.2 ,181.4,181.3,181
XS GIS Cut Line= 3
     1679623.283      715977.457      1679547.18      715900.591
     1678989.871      716265.916
#Sta/Elev= 30
       0  905.55    19.7  897.29      59  879.47    68.8  873.17    88.5  858.64
    98.3  853.69   108.2  851.59     118  850.06   137.6  847.93   284.6  837.06
   304.2  834.95     314  834.54     330 835.192   350.5836.0184   519.8  839.62
   529.6  840.01   539.4  842.04   549.2  846.79     559  852.26   578.6  864.05
   598.2   876.9   637.4  904.63     657  918.14   676.5  930.47   696.1  941.41
   705.9  946.15   715.7  950.23   725.5  953.72   745.1  959.78   774.5  966.81
#Mann= 3 , 0 , 0
       0      .1       0     330    .045       0   350.5     .08       0
Bank Sta=330,350.5
XS Rating Curve= 0 ,0
Exp/Cntr=0.3,0.1

Type RM Length L Ch R = 1 ,13414   ,440.4,438.2,435.5
XS GIS Cut Line= 2
     1679517.296      715702.511      1678987.49      716058.289
#Sta/Elev= 30
       0  880.74    58.9   852.3    68.7  848.23    78.6  845.83    88.4  844.54
    98.2  843.76     108  843.46   127.6  843.45   147.3  843.63   166.9  843.54
   186.5  843.17   196.4   842.7   206.2  842.11   225.8  840.53   255.3  837.67
   274.9  836.03   294.5  834.68   310.7834.0001   314.2   833.9     324  834.03
   337.7834.5871   402.5  837.78   481.1  839.46   490.9  839.94   500.7   842.4
   510.5  846.81   520.4  852.12     540  862.95   589.1  890.49   638.2  918.62
#Mann= 3 , 0 , 0
       0      .1       0   310.7    .045       0   337.7      .1       0
Bank Sta=310.7,337.7
XS Rating Curve= 0 ,0
Exp/Cntr=0.3,0.1

Type RM Length L Ch R = 1 ,12975.8 ,391.4,386.8,382.5
XS GIS Cut Line= 3
     1679361.187      715286.681     1678878.073      715642.477
     1678808.489      715729.093
#Sta/Elev= 30
       0  955.21    19.7  942.45    49.2  922.41     118  874.52   147.5  854.32
   167.2  841.34     177  836.06   186.9  833.31   196.7  832.48   255.7  831.61
   311.2  830.26   340.2829.8324   344.3  829.82   363.9  829.86   373.8  830.33
   403.3  834.19   442.6  838.76   521.3  847.21   531.1  848.09     541  848.66
   550.8   850.3   560.6  854.02   590.2  869.72     600   874.4   609.2  878.44
   618.5  882.11   627.8  886.28   646.3  895.45   692.6  917.29   711.1  926.44
#Mann= 3 , 0 , 0
       0      .1       0   311.2    .045       0   340.2      .1       0
Bank Sta=311.2,340.2
XS Rating Curve= 0 ,0
Exp/Cntr=0.3,0.1

Type RM Length L Ch R = 1 ,12589   ,475.4,464.6,452.8
XS GIS Cut Line= 3
      1679114.65      714907.678     1678716.131      715407.638
     1678581.927      715479.527
#Sta/Elev= 30
       0 1005.97    19.7  996.07   108.2  948.92   265.6  852.53   275.4  846.36
   285.2  839.68   295.1  832.23   304.9  826.74   314.8  825.16   324.6  825.93
   363.9  833.17   383.6  835.31   403.3  836.88   452.5  839.37   511.5  840.54
     541  841.57   580.3  844.33   590.2  845.21     600   846.6   609.8  849.03
   629.5  857.02   639.4  860.02   648.9  861.74   658.4  864.24   667.9  868.26
   715.5  891.73   734.5  900.41   763.1  912.04   782.1  918.88   791.6  921.93
#Mann= 3 , 0 , 0
       0      .1       0   304.9    .045       0   324.6      .1       0
Bank Sta=304.9,324.6
XS Rating Curve= 0 ,0
Exp/Cntr=0.3,0.1

Type RM Length L Ch R = 1 ,12124.4 ,416.9,426.9,436.3
XS GIS Cut Line= 4
     1678604.891      714807.657     1678520.983      714893.491
     1678469.879       715176.22      1678341.87      715460.001
#Sta/Elev= 30
       0  917.01     9.2  916.14    18.5  913.69    27.7  908.28    36.9  900.64
    83.1  858.37   101.6  840.43   110.8   834.3     120  831.86   139.2  831.22
   158.3  829.99   233.5823.1178   244.5  822.87   263.5  824.29     302  828.36
   321.2  829.75   340.3  830.42   378.6  829.87   397.8  830.19   407.3  831.34
   426.8  836.02   465.7  846.35   485.2  852.17     563  885.23   572.7  888.75
   582.5     891   592.2  892.38   601.9  895.08   650.6  914.91   718.7  944.22
#Mann= 3 , 0 , 0
       0      .1       0   233.5    .045       0   263.5      .1       0
Bank Sta=233.5,263.5
XS Rating Curve= 0 ,0
Exp/Cntr=0.3,0.1

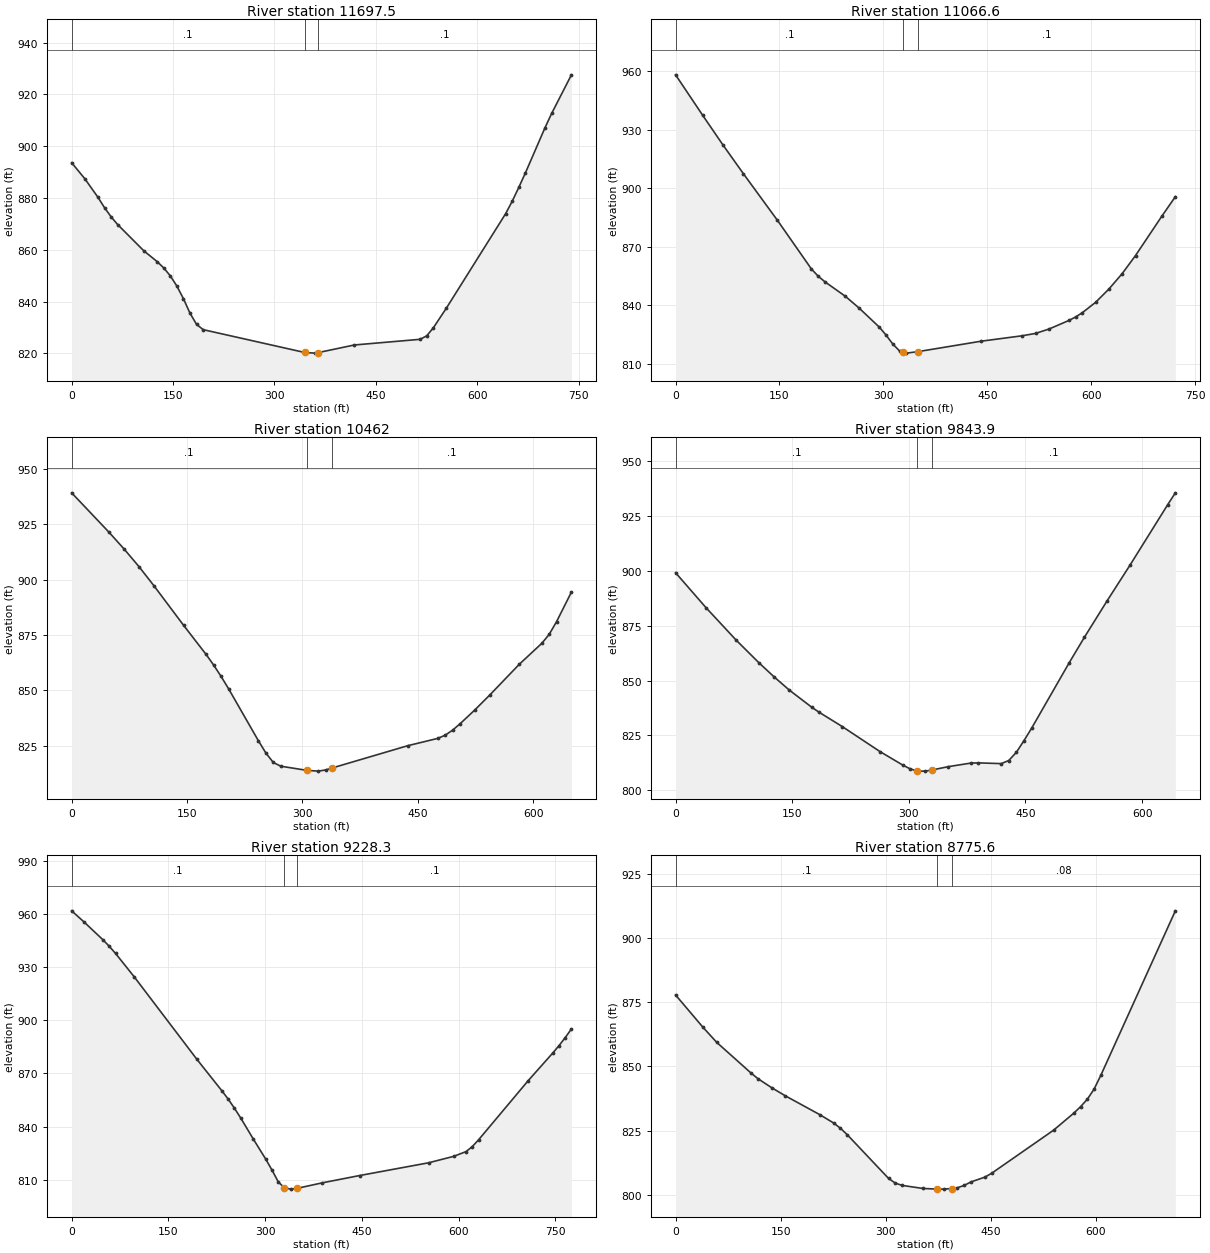
Type RM Length L Ch R = 1 ,11697.5 ,634.4,630.9,626.2
XS GIS Cut Line= 2
     1678361.684      714545.676      1677947.62      715158.207
#Sta/Elev= 30
       0  893.63    19.5  887.44    38.9  880.28    48.6  876.27    58.4  872.72
    68.1  869.73     107  859.54   126.5  855.43   136.2     853   145.9  849.94
   155.6  846.01   165.4   841.1   175.1  835.49   184.8  831.18   194.6  829.14
   344.8820.3181     360  820.07   364.8  820.28   418.3  823.22   515.6  825.41
   525.3  826.76   535.1  829.84   554.5   837.5   642.1  873.96   651.8  878.75
   661.5  884.08   671.3  889.68   700.4  907.21   710.2   912.7   739.4  927.59
#Mann= 3 , 0 , 0
       0      .1       0   344.8    .045       0   364.8      .1       0
Bank Sta=344.8,364.8
XS Rating Curve= 0 ,0
Exp/Cntr=0.3,0.1

Type RM Length L Ch R = 1 ,11066.6 ,600.6,604.6,607.8
XS GIS Cut Line= 3
     1677862.562      714207.126     1677634.521      714695.754
      1677492.94      714810.586
#Sta/Elev= 30
       0  958.22    39.2  937.42    68.6  922.16      98  907.47   147.1  883.58
   196.1  858.65   205.9  854.95   215.7  852.06   245.1  844.66   264.7  838.69
   294.1  828.85   303.9  824.73   313.7  820.14   323.5  816.56     329815.9711
   333.3  815.51     350816.2784   441.2  821.63     500  824.39   519.6  825.61
   539.2  827.88     568  832.29   577.6  834.07   587.2  836.24   606.4  841.57
   625.6  848.38   644.8  856.31     664  865.56   702.3   885.9   721.5  895.74
#Mann= 3 , 0 , 0
       0      .1       0     329    .045       0     350      .1       0
Bank Sta=329,350
XS Rating Curve= 0 ,0
Exp/Cntr=0.3,0.1

Type RM Length L Ch R = 1 ,10462   ,605.3,618,628.5
XS GIS Cut Line= 3
      1677365.56      714005.938      1677087.98      714415.914
     1676969.995      714515.635
#Sta/Elev= 30
       0  939.15    48.5  921.38      68  913.86    87.4  905.89   106.8  897.28
   145.6  879.31   174.7  866.24   184.4  861.51   194.2  856.31   203.9  850.77
   242.7  827.28   252.4  821.76   262.1  817.45   271.8  815.78   305.5813.9066
   320.4  813.55   330.1  814.07   338.5814.9619   436.9  825.03   475.7  828.31
   485.4  829.75   495.1  832.02   504.8  834.91   524.1  841.18   543.4  847.88
     582  861.83     611  871.19   620.6  875.22   630.3  881.02   649.6  894.36
#Mann= 3 , 0 , 0
       0      .1       0   305.5    .045       0   338.5      .1       0
Bank Sta=305.5,338.5
XS Rating Curve= 0 ,0
Exp/Cntr=0.3,0.1

Type RM Length L Ch R = 1 ,9843.9  ,620,615.7,609.9
XS GIS Cut Line= 2
     1677119.241      713711.773     1676550.024      714010.405
#Sta/Elev= 30
       0  899.16      39  883.29    77.9  868.45   107.1  858.16   126.6  851.74
   146.1  845.73   175.3  837.82     185   835.5   214.3  829.08     263  817.64
   292.2  811.51   301.9  809.74     311808.8207   311.7  808.75   321.4  808.76
     330 809.284   350.6  810.78   379.8  812.42   389.6  812.51   418.8  812.17
   428.5  813.58   438.3  817.32     448  822.58   457.8  828.23   506.4  858.22
   525.9   869.8   555.1   886.4   584.4  902.58   633.1  930.25   642.8  935.57
#Mann= 3 , 0 , 0
       0      .1       0     311    .045       0     330      .1       0
Bank Sta=311,330
XS Rating Curve= 0 ,0
Exp/Cntr=0.3,0.1

Type RM Length L Ch R = 1 ,9228.3  ,455.7,452.7,450.1
XS GIS Cut Line= 3
     1676831.971      713185.943     1676366.349      713582.788
     1676211.184      713633.786
#Sta/Elev= 30
       0  961.75    19.4   955.4    48.6  945.38    58.3  941.74      68  937.74
    97.1  924.47   194.2  877.96   233.1  860.13   242.8  855.48   252.5  850.33
   262.2  844.83   281.6  833.02     301  821.61   310.8  815.37   320.5  808.74
     330805.4102   339.9  804.68     350805.1525   388.4  808.21   446.7  812.36
   553.5  819.54   592.4  823.17   611.8  825.88   621.4  828.72     631  832.47
   707.9  865.84   746.3  881.56   755.9   885.7   765.5   890.2   775.1   895.1
#Mann= 3 , 0 , 0
       0      .1       0     330    .045       0     350      .1       0
Bank Sta=330,350
XS Rating Curve= 0 ,0
Exp/Cntr=0.3,0.1

Type RM Length L Ch R = 1 ,8775.6  ,675.4,688.9,698.4
XS GIS Cut Line= 4
     1676557.075      713028.881     1676343.628       713059.44
     1676104.525      713263.166     1675970.053      713388.039
#Sta/Elev= 30
       0  877.77    39.2  865.15    58.8   859.3   107.8  847.35   117.6  845.17
   137.2  841.66   156.8  838.48   205.8  831.18   225.4  827.96   235.3  825.88
   245.1  823.34     304  806.34   313.8  804.49   323.6  803.62     353  802.44
     373802.1995   382.5  802.18     395802.4191   402.1   802.7     412  803.64
   421.8  805.01   441.4  806.84   451.2  808.37   539.4  825.11   568.4  831.77
     578  834.28   587.7  837.19   597.4  841.16     607  846.54   713.3  910.53
#Mann= 3 , 0 , 0
       0      .1       0     373    .045       0     395     .08       0
Bank Sta=373,395
XS Rating Curve= 0 ,0
Exp/Cntr=0.3,0.1

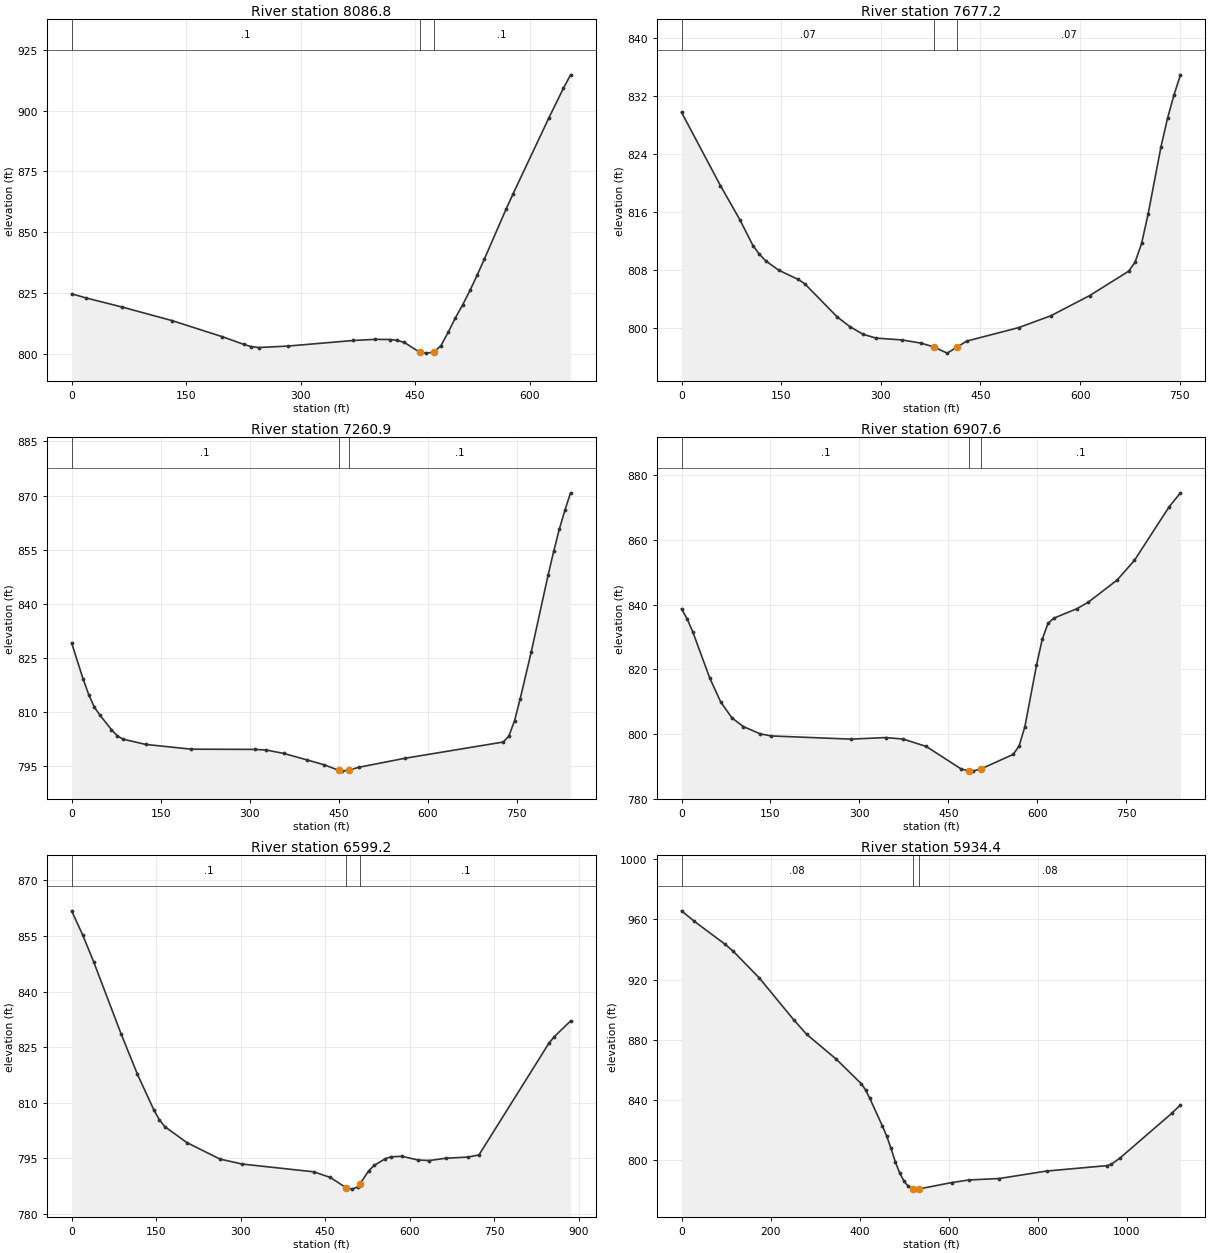
Type RM Length L Ch R = 1 ,8086.8  ,411.5,409.6,392.6
XS GIS Cut Line= 4
     1676323.252      712758.936     1676137.344       712733.85
     1675826.313      712828.151     1675706.065      712902.165
#Sta/Elev= 30
       0  824.63    18.8  822.93    65.7  819.21   131.3  813.62   197.2  806.99
   225.8  803.78   235.4  802.88     245  802.51   283.2   803.1   369.2  805.41
   397.9  805.87     417   805.8   426.6  805.46   436.1   804.6   455.2  800.75
     457 800.645   464.8   800.2   474.4  800.58   483.9  803.26   493.5  808.82
     503  814.78   512.6   820.2     522  826.03   531.4  832.28   540.8   838.9
   569.1  859.33   578.5  865.81   625.6   897.2   644.4  909.22   653.8  914.77
#Mann= 3 , 0 , 0
       0      .1       0     457    .045       0   474.4      .1       0
Bank Sta=457,474.4
XS Rating Curve= 0 ,0
Exp/Cntr=0.3,0.1

Type RM Length L Ch R = 1 ,7677.2  ,413.3,416.3,430.5
XS GIS Cut Line= 3
     1676402.388      712561.743      1676280.03      712481.106
     1675675.809      712461.996
#Sta/Elev= 30
       0  829.72    58.6  819.61    87.9   814.9   107.5  811.36   117.2  810.16
     127  809.23   146.5  807.95   175.8  806.68   185.5  806.09   234.3  801.53
   253.8  800.16   273.3  799.13   292.8   798.6   331.8  798.35     361   797.9
   379.4797.3928     400  796.53   414.4 797.338   429.3  798.19   507.3  800.04
     556  801.68   614.6  804.47   673.1  807.82   682.8  809.07   692.6  811.66
   702.3  815.65   721.8  824.98   731.6  828.88   741.3   832.1   751.1  834.88
#Mann= 3 , 0 , 0
       0     .07       0   379.4    .045       0   414.4     .07       0
Bank Sta=379.4,414.4
XS Rating Curve= 0 ,0
Exp/Cntr=0.3,0.1

Type RM Length L Ch R = 1 ,7260.9  ,329.2,353.3,376.4
XS GIS Cut Line= 4
     1676446.342      712241.075     1676271.444       712140.49
     1675754.534      712236.875     1675641.577      712227.993
#Sta/Elev= 30
       0  829.22    19.2  819.29    28.8  814.89    38.4   811.4      48  809.13
    67.2  805.16    76.9  803.49    86.5  802.54   124.9  801.08   201.8  799.76
   308.9   799.7   328.4  799.52   357.6  798.58   396.5   796.8   425.7  795.43
   449.9793.9315   454.9  793.68   466.9  793.94   484.1  794.75     562  797.25
   727.6  801.75     737  803.44   746.5  807.64   755.9  813.65   774.8  826.82
   803.1  848.03   812.6  854.64     822  860.74   831.4  865.99   840.9  870.78
#Mann= 3 , 0 , 0
       0      .1       0   449.9    .045       0   466.9      .1       0
Bank Sta=449.9,466.9
XS Rating Curve= 0 ,0
Exp/Cntr=0.3,0.1

Type RM Length L Ch R = 1 ,6907.6  ,316.7,308.5,300.1
XS GIS Cut Line= 4
     1676482.249      712225.632     1676280.162      712102.202
      1676003.99      711824.983     1675790.843      711838.913
#Sta/Elev= 30
       0  838.77     9.5  835.65    18.9  831.68    47.4  817.45    66.3  809.87
    85.2     805   104.2  802.35   132.6  800.08   151.6  799.43   285.7  798.45
   344.4  798.93   373.8  798.47   412.9  796.18   471.6  789.23     485788.5856
   491.2  788.55     506 789.299   559.6  793.74   569.4   796.3   579.2  802.28
   598.8  821.26   608.5  829.33   618.3  834.26   628.1  835.86   666.9  838.79
   686.4  840.83   734.9  847.67     764  853.73   822.3  870.23   841.7  874.63
#Mann= 3 , 0 , 0
       0      .1       0     485    .045       0     506      .1       0
Bank Sta=485,506
XS Rating Curve= 0 ,0
Exp/Cntr=0.3,0.1

Type RM Length L Ch R = 1 ,6599.2  ,687.9,664.7,640.3
XS GIS Cut Line= 4
     1676743.362      711823.984      1676577.84       711827.76
     1676080.265      711576.395     1675972.529      711698.116
#Sta/Elev= 30
       0   861.8    19.5  855.34      39  848.09    87.6  828.66   116.9  817.64
   146.1  807.99   155.8  805.35   165.6  803.49   204.7   799.2   263.4  794.75
   302.5  793.42   429.6  791.32     459   789.8     487787.0593   498.1  786.64
   507.9  787.26     512788.1033   527.4  791.62   537.2  793.06   556.8  794.86
   566.6  795.37   586.1   795.5   615.4   794.5     635  794.37   664.4  794.98
   703.5   795.3     723  795.87   847.3  826.08   856.9  827.84   885.6  832.05
#Mann= 3 , 0 , 0
       0      .1       0     487    .045       0     512      .1       0
Bank Sta=487,512
XS Rating Curve= 0 ,0
Exp/Cntr=0.3,0.1

Type RM Length L Ch R = 1 ,5934.4  ,305.7,305.8,305.4
XS GIS Cut Line= 5
     1676672.832       710832.99     1676489.774      711046.468
     1676390.789       711196.38     1676009.025      711446.228
     1675850.784       711574.31
#Sta/Elev= 30
       0  965.68    29.1  958.63      97  943.65   116.4  938.74   174.6  921.08
   252.1  893.19   281.2  883.51   347.4  867.08   404.1  850.61   413.6  846.45
     423   840.9   451.4  822.44   460.9  815.82   470.6  807.66   480.3  798.66
     490  791.38   499.7     786   509.4   782.4   519.1  780.68   528.8   780.6
     534780.7812   606.5  784.94   645.3  786.68   713.3  787.65     820  792.62
   955.9  796.24   965.6  797.17     985  801.31  1101.3  831.07  1120.7  836.66
#Mann= 3 , 0 , 0
       0     .08       0   519.1    .045       0     534     .08       0
Bank Sta=519.1,534
XS Rating Curve= 0 ,0
Exp/Cntr=0.3,0.1

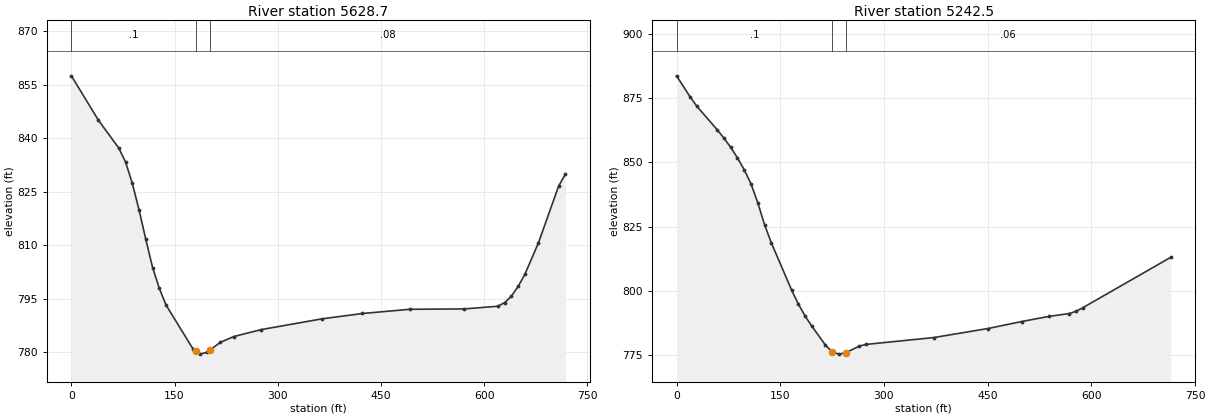
Type RM Length L Ch R = 1 ,5628.7  ,391.3,386.2,381
XS GIS Cut Line= 2
     1676296.079      710900.625     1675696.409      711295.886
#Sta/Elev= 30
       0  857.44    39.4  844.97    68.9  837.19    78.7   833.3    88.6   827.3
    98.4  819.85   108.2   811.6   118.1   803.7   127.9  797.83   137.7  793.16
   177.1   780.8   180.5  780.32   186.9  779.43   196.8  779.92   201.5780.5626
   216.4  782.72   236.1  784.36   275.5  786.29     364  789.31   423.1  790.82
   491.9     792   570.6   792.1   619.8  792.85   629.7  793.85   639.5  795.65
   649.4   798.4   659.2  801.79   678.9  810.61   708.4  826.59   718.2  829.92
#Mann= 3 , 0 , 0
       0      .1       0   180.5    .045       0   201.5     .08       0
Bank Sta=180.5,201.5
XS Rating Curve= 0 ,0
Exp/Cntr=0.3,0.1

Type RM Length L Ch R = 1 ,5242.5  ,326.7,330.1,333.4
XS GIS Cut Line= 3
     1676083.622      710516.217     1675710.869      710904.996
     1675581.769      711024.575
#Sta/Elev= 30
       0  883.66    19.6   875.5    29.4  871.84    58.8  862.71    68.6  859.44
    78.3  855.85    88.1   851.8    97.9  847.14   107.7  841.66   117.5  834.33
   127.3  825.81   137.1  818.75   166.5  800.34   176.3  794.91   186.1  790.22
   195.9  786.29   215.4  778.99   225.2  776.31     235   775.5   244.8  776.07
   264.4  778.62   274.2  779.28   372.1  781.94   450.5  785.46   499.4  788.18
   538.6  790.16   567.9  791.28   577.7  792.12   587.5  793.52   714.6   813.1
#Mann= 3 , 0 , 0
       0      .1       0   225.2    .045       0   244.8     .06       0
Bank Sta=225.2,244.8
XS Rating Curve= 0 ,0
Exp/Cntr=0.3,0.1