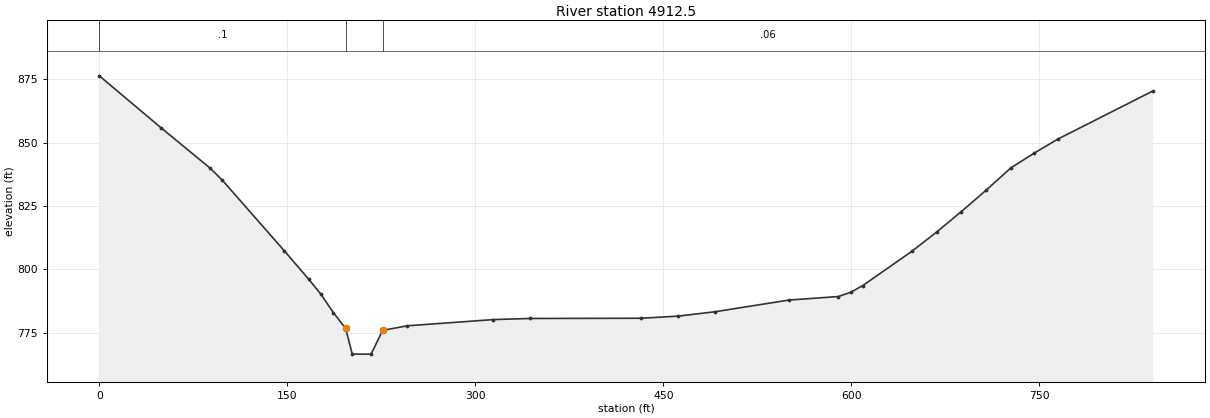
HEC-RAS study NFKINGSCK.prj: NFKINGSCK

--- NFKINGSCK.g01 (geometry) --- (continued)

Type RM Length L Ch R = 1 ,4912.5  ,4932.4,4912.5,4883.2
XS GIS Cut Line= 3
     1675854.249      710325.102     1675281.863      710773.394
     1675169.042      710762.501
#Sta/Elev= 30
       0  876.36    49.1   855.9    88.4  839.91    98.2  835.12   147.4  807.38
     167  796.09   176.8  790.13   186.7  782.89   196.5  776.63   201.8   766.5
   216.8   766.5     226  775.88   245.6  777.68   314.4  780.14   343.9  780.58
   432.3  780.66   461.8  781.51   491.2  783.23   550.2  787.85   589.5  789.23
   599.3  790.88   609.1  793.57   648.4  807.16   668.1  814.72   687.7  822.78
   707.4  831.18     727  839.94   745.9  845.86   764.8  851.42   840.4  870.35
#Mann= 3 , 0 , 0
       0      .1       0   196.5    .045       0     226     .06       0
Bank Sta=196.5,226
XS Rating Curve= 0 ,0
Exp/Cntr=0.3,0.1

Chan Stop Cuts=-1
Use User Specified Reach Order=0
Composite Channel Slope=5

--- NFKINGSCK.g09 (geometry) ---

Geom Title=USGS 10m DEM
Program Version=4.10

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
River Reach=NFKINGSCK       ,Main

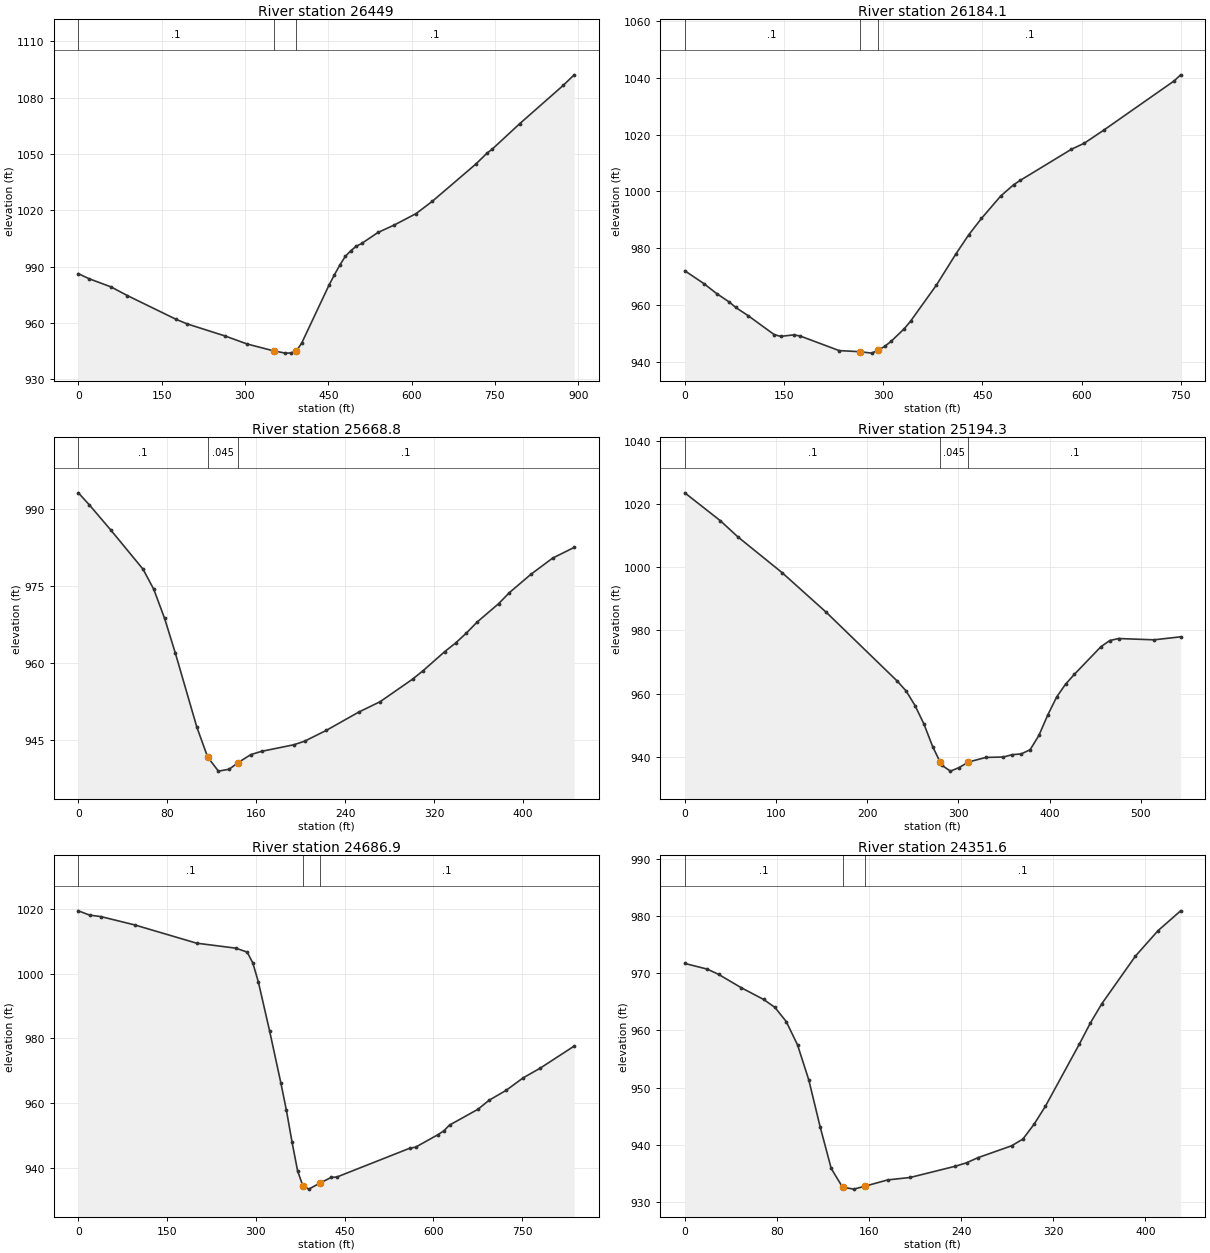
Type RM Length L Ch R = 1 ,26449   ,22307.3,265,22252.7
XS GIS Cut Line= 2
     1685002.035      722393.678     1685026.341      723286.039
#Sta/Elev= 30
       0   986.3    19.6  983.57    58.9  979.24    88.3  974.63   176.6  961.91
   196.2  959.53   264.9  953.06   304.1  948.84   351.8  945.19   372.8     944
   382.6  944.07   392.4  945.07   402.2  949.38   451.2  980.12   461.1   985.7
   470.9  990.93   480.7  995.52   490.5  998.48   500.3 1000.86   510.1 1002.36
   539.5 1008.22     569 1012.21   608.2 1018.28   637.6 1024.88   716.1 1044.73
   735.7 1050.41   745.6 1052.67   794.6  1066.1   873.1 1086.52   892.7 1092.12
#Mann= 3 , 0 , 0
       0      .1       0   351.8    .045       0   392.4      .1       0
Bank Sta=351.8,392.4
XS Rating Curve= 0 ,0
Exp/Cntr=0.3,0.1

Type RM Length L Ch R = 1 ,26184.1 ,22307.3,515.3,22252.7
XS GIS Cut Line= 4
     1684960.369      722459.651     1684918.702      722556.873
     1684693.008      722695.762     1684335.369      722820.762
#Sta/Elev= 30
       0  972.09    28.8  967.59    48.1  964.07    67.3  961.09    76.9   959.2
    96.2  956.22   135.2  949.62     145     949   164.7  949.54   174.5  949.13
   233.4     944   264.3  943.62   282.4  943.11   292.3  944.12   302.1  945.47
   311.9  947.26   331.5  951.63   341.3  954.34   380.5  967.09   409.6  977.92
   429.1  984.69   448.5   990.5   477.6  998.39   497.1 1002.34   506.8 1003.85
   584.5 1014.84   603.9 1016.96   633.1 1021.52   739.9 1038.91   749.6 1041.03
#Mann= 3 , 0 , 0
       0      .1       0   264.3    .045       0   292.3      .1       0
Bank Sta=264.3,292.3
XS Rating Curve= 0 ,0
Exp/Cntr=0.3,0.1

Type RM Length L Ch R = 1 ,25668.8 ,22307.3,474.4,22252.7
XS GIS Cut Line= 2
     1684901.341      722164.512     1684474.258      722292.984
#Sta/Elev= 30
       0  993.14     9.7  990.85    29.1  985.93    58.2  978.29    67.9  974.36
    77.6  968.71    87.3  961.94   106.6  947.57   116.3  941.76     126  939.01
   135.7  939.38   143.6  940.65   155.1  942.22   164.8  942.86   193.9  944.14
   203.6  944.84     223  946.93   252.1  950.48   271.5  952.52   300.6  956.89
   310.2  958.56   329.6  962.26   339.3  963.92     349  965.85   358.7     968
   378.1  971.59   387.8  973.74   407.2  977.31   426.6  980.44     446  982.52
#Mann= 3 , 0 , 0
       0      .1       0   116.3    .045       0   143.6      .1       0
Bank Sta=116.3,143.6
XS Rating Curve= 0 ,0
Exp/Cntr=0.3,0.1

Type RM Length L Ch R = 1 ,25194.3 ,22307.3,507.4,22252.7
XS GIS Cut Line= 2
     1684904.813      721643.678     1684401.341      721848.539
#Sta/Elev= 30
       0 1023.53    38.8 1014.75    58.2  1009.6   106.8  998.26   155.3   985.7
     233  963.98   242.7  960.86   252.4  956.27   262.1  950.48   271.8  943.25
     280  938.36   281.5  937.46   291.2  935.53   300.9  936.67   310.6  938.38
     330  939.86   349.4     940   359.1  940.74   368.8  940.97   378.6   942.3
   388.2  946.82     398  953.32   407.7  958.97   417.4     963   427.1  966.14
   456.2  974.87   465.9  976.82   475.6  977.46   514.4  977.05   543.6     978
#Mann= 3 , 0 , 0
       0      .1       0     280    .045       0   310.6      .1       0
Bank Sta=280,310.6
XS Rating Curve= 0 ,0
Exp/Cntr=0.3,0.1

Type RM Length L Ch R = 1 ,24686.9 ,22307.3,335.4,22252.7
XS GIS Cut Line= 4
     1684276.341      721015.206     1684297.174      721299.928
     1684356.202      721529.095     1684349.258      721845.067
#Sta/Elev= 30
       0 1019.38      19 1018.06    38.1  1017.6    95.2 1015.03   199.8 1009.39
   266.4 1007.84   285.5 1006.62     295 1003.25   304.4  997.36   323.4  982.22
   342.3  966.26   351.7   957.8   361.2     948   370.7     939   379.5  934.43
   389.6  933.38   408.5  935.26   427.5     937   436.9  937.11   560.4  946.03
     570  946.34   608.3  950.24   617.9   951.4   627.5  953.17   675.4  958.04
   694.5  960.86   723.2  963.91     752  967.77   780.7  970.75   838.2  977.58
#Mann= 3 , 0 , 0
       0      .1       0   379.5    .045       0   408.5      .1       0
Bank Sta=379.5,408.5
XS Rating Curve= 0 ,0
Exp/Cntr=0.3,0.1

Type RM Length L Ch R = 1 ,24351.6 ,22307.3,488.5,22252.7
XS GIS Cut Line= 2
     1683967.313      721362.428     1684088.841      721775.623
#Sta/Elev= 30
       0  971.71    19.6  970.71    29.4  969.79    48.9  967.48    68.5  965.41
    78.3  964.02    88.1  961.55    97.9  957.48   107.7  951.34   117.5  943.19
   127.2  935.85     137  932.59   137.7  932.56   146.8  932.24   156.6  932.76
   176.2  933.85   195.8  934.28   234.9  936.24   244.7  936.84   254.5  937.73
   283.9  939.82   293.7     941   303.4  943.59   313.2  946.72   342.6  957.56
   352.4  961.33   362.2  964.65   391.5  973.01   411.1  977.45   430.7  980.91
#Mann= 3 , 0 , 0
       0      .1       0   137.7    .045       0   156.6      .1       0
Bank Sta=137.7,156.6
XS Rating Curve= 0 ,0
Exp/Cntr=0.3,0.1

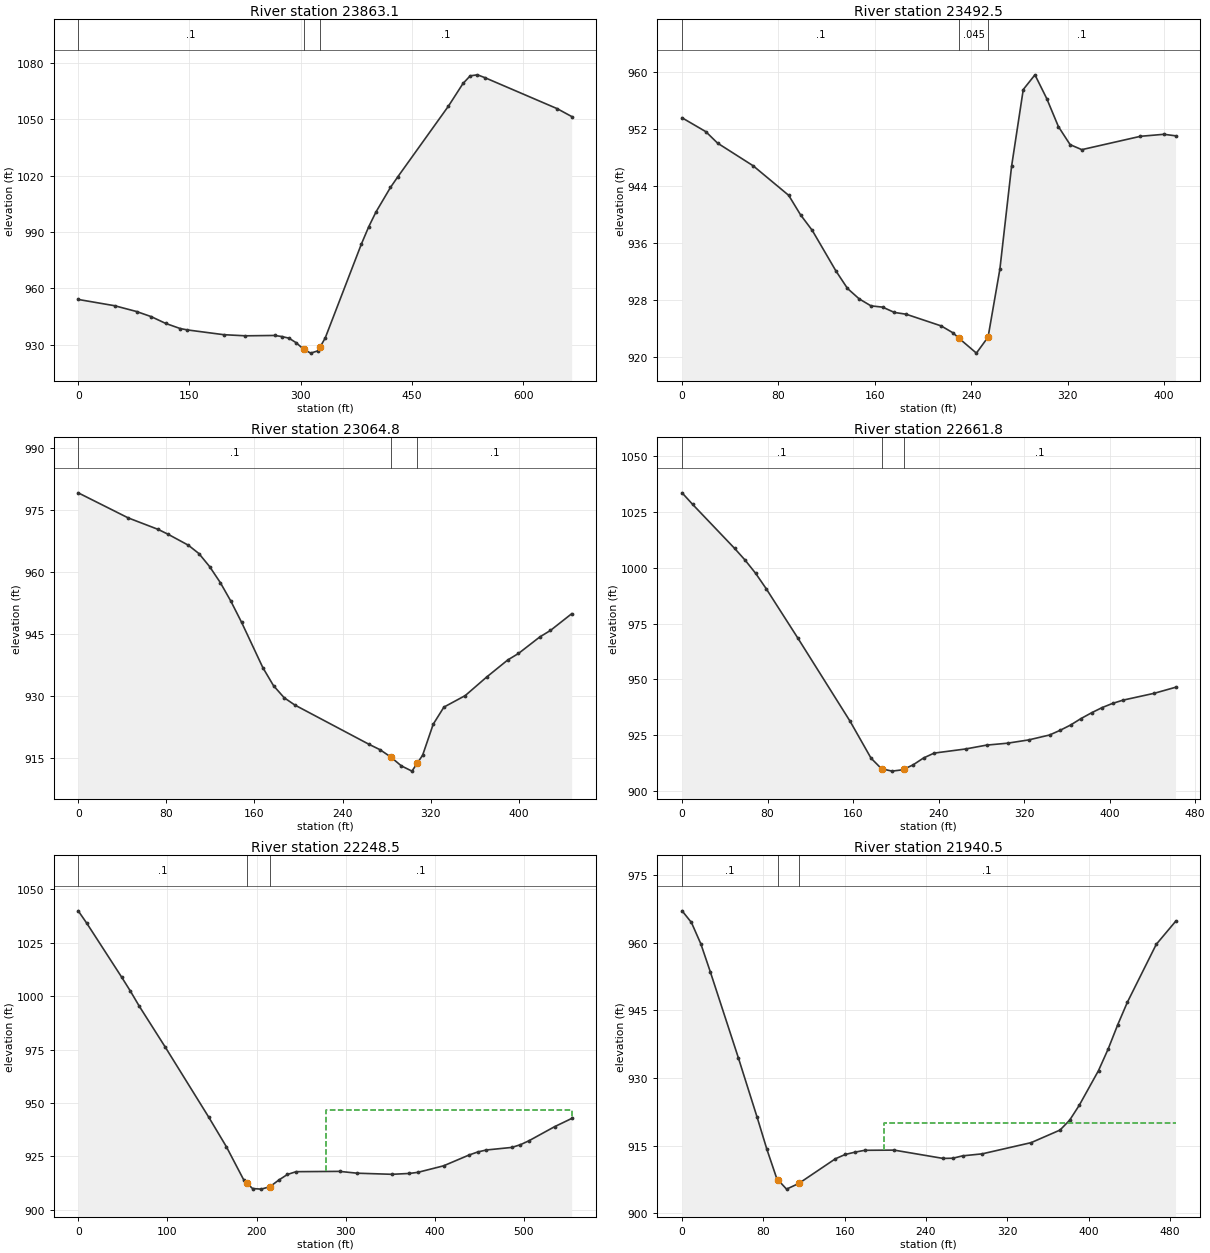
Type RM Length L Ch R = 1 ,23863.1 ,22307.3,370.6,22252.7
XS GIS Cut Line= 3
     1683786.758      721376.317     1683699.952      721470.067
     1683286.758      721813.817
#Sta/Elev= 30
       0  954.04    49.1   950.7    78.6  947.62    98.3  944.91   117.9  941.28
   137.5  938.55   147.3  937.81   196.2  935.28   225.5  934.68   264.6  934.87
   274.4   934.3   284.1  933.43   293.9  930.97   303.7  927.57   313.4  925.46
   323.2  926.69   326.1  928.72     333  933.56   381.8  983.63   391.6  992.73
   401.4 1000.63   420.9 1013.67   430.7 1019.28   499.1    1057   518.7 1069.04
   528.4 1073.11   538.2 1073.65     548 1072.18   645.7 1055.63   665.2 1051.45
#Mann= 3 , 0 , 0
       0      .1       0   303.7    .045       0   326.1      .1       0
Bank Sta=303.7,326.1
XS Rating Curve= 0 ,0
Exp/Cntr=0.3,0.1

Type RM Length L Ch R = 1 ,23492.5 ,22307.3,427.7,22252.7
XS GIS Cut Line= 3
     1683752.035      721272.151     1683644.396      721261.734
      1683352.73      721185.345
#Sta/Elev= 30
       0  953.54    19.7   951.6    29.5  949.99      59  946.82    88.5  942.68
    98.3  939.96   108.1  937.76   127.6  932.12   137.3  929.64     147  928.18
   156.8   927.2   166.5  927.02   176.2  926.28     186  926.03   215.1  924.39
   224.8  923.43   229.8  922.67   244.3  920.58     254  922.83   263.8  932.35
   273.5  946.74   283.2   957.5   292.9  959.56   302.7  956.23   312.4   952.3
   322.1  949.78   331.8  949.08   380.5  950.95   399.9  951.23   409.6  951.02
#Mann= 3 , 0 , 0
       0      .1       0   229.8    .045       0     254      .1       0
Bank Sta=229.8,254
XS Rating Curve= 0 ,0
Exp/Cntr=0.3,0.1

Type RM Length L Ch R = 1 ,23064.8 ,22307.3,403,22252.7
XS GIS Cut Line= 3
     1683887.452      720952.706     1683793.702      720917.984
     1683488.146      720751.317
#Sta/Elev= 30
       0  979.06    45.4     973    72.7  970.21    81.8  969.02     100   966.4
   109.6  964.38   119.3  961.24     129  957.37   138.6  952.87   148.3  947.78
   167.6  936.83   177.3  932.46     187  929.54   196.7  927.78   264.3  918.25
     274  916.99   283.7  915.24   293.3  913.09     303  911.81     308   913.8
   312.7  915.67   322.3  923.15     332  927.28   351.4  930.07   370.7  934.52
     390  938.68   399.7  940.24     419  944.22   428.7   945.8     448  949.84
#Mann= 3 , 0 , 0
       0      .1       0   283.7    .045       0     308      .1       0
Bank Sta=283.7,308
XS Rating Curve= 0 ,0
Exp/Cntr=0.3,0.1

Type RM Length L Ch R = 1 ,22661.8 ,58.9,413.2,57.4
XS GIS Cut Line= 2
     1683873.563      720348.539     1683470.785      720574.234
#Sta/Elev= 30
       0 1033.46     9.8 1028.33    49.1 1008.64    58.9 1003.41    68.8  997.48
    78.6  990.67   108.1  968.67   157.2  931.32   176.8  914.82   186.6  910.09
   196.5  909.03   206.3  909.63   207.6  909.92   216.1  911.81   225.9   914.9
   235.8  917.09   265.2  918.93   284.9  920.66   304.5  921.52   324.2  922.98
   343.8  925.18   353.6  927.26   363.5  929.64   373.3  932.55   383.1  935.11
   392.9  937.42   402.8  939.31   412.6  940.77     442  943.86   461.7  946.52
#Mann= 3 , 0 , 0
       0      .1       0   186.6    .045       0   207.6      .1       0
Bank Sta=186.6,207.6
XS Rating Curve= 0 ,0
Exp/Cntr=0.3,0.1

Type RM Length L Ch R = 1 ,22248.5 ,327.7,308,287.9
XS GIS Cut Line= 3
     1683639.682      719962.868     1683360.199      720207.539
     1683339.251      720388.367
#Sta/Elev= 30
       0 1039.99     9.8 1034.06    48.9 1008.83    58.6 1002.36    68.4   995.4
    97.8  976.08   146.6  943.25   166.2  929.54   185.7  913.98   189.3  912.51
   195.5  909.97   205.3  909.69     215  910.82   224.8  913.88   234.6  916.55
   244.4  917.86   293.2     918   312.8  917.15   351.9  916.63   371.4  917.03
     381  917.55   409.8   920.6   438.5  925.68   448.1  927.08   457.7  928.01
   486.4  929.22     496  930.49   505.6  932.34   534.3  938.92   553.5  942.77
#Mann= 3 , 0 , 0
       0      .1       0   189.3    .045       0     215      .1       0
#XS Ineff= 2 , 0
                          277.95          946.79
Permanent Ineff=
       F       F
Bank Sta=189.3,215
XS Rating Curve= 0 ,0
Exp/Cntr=0.3,0.1

Type RM Length L Ch R = 1 ,21940.5 ,328.7,350.9,369.8
XS GIS Cut Line= 4
     1683238.381      719872.441     1683213.381      719941.978
     1683220.345       720211.46     1683144.577      720331.723
#Sta/Elev= 30
       0  967.12     9.2  964.53    18.5  959.76    27.7  953.64    55.4  934.48
    73.9  921.26    83.5  914.15    93.2  907.68    94.3 907.411   102.8  905.34
   114.8 906.593   150.9  912.08   160.5  913.03   170.2  913.55   179.8  913.96
   208.7     914   256.8  912.16   266.4   912.2   276.1  912.73   295.3  913.17
   343.5  915.66   371.9  918.45   381.4  920.65   390.8  923.94   409.8  931.66
   419.3  936.45   428.8  941.88   438.2  946.83   466.6  959.67   485.6  964.77
#Mann= 3 , 0 , 0
       0      .1       0    94.3    .045       0   114.8      .1       0
#XS Ineff= 2 , 0
       0                     199       0     920
Permanent Ineff=
       F       F
Bank Sta=94.3,114.8
XS Rating Curve= 0 ,0
Exp/Cntr=0.3,0.1

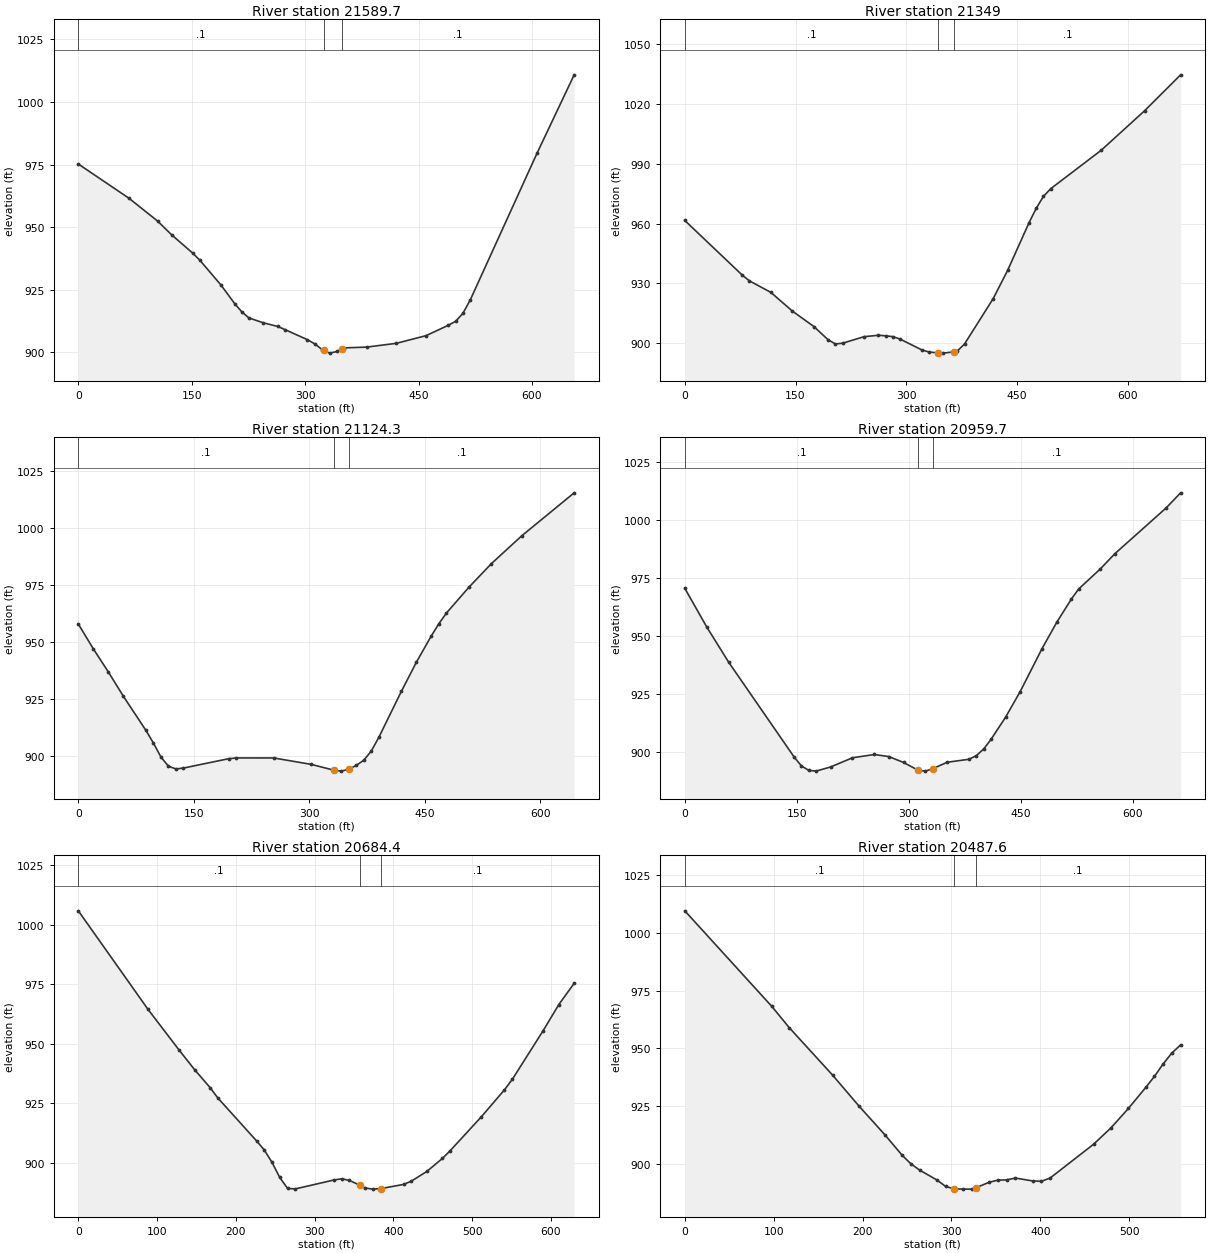
Type RM Length L Ch R = 1 ,21589.7 ,232,240.7,248.8
XS GIS Cut Line= 4
     1683267.358      719823.364     1683162.563      719825.064
     1683027.826      719789.453     1682719.465      720062.188
#Sta/Elev= 30
       0  975.24    66.7  961.63   104.8  952.47   123.4  946.97   151.3  939.64
   160.6  936.86   188.4     927     207  919.39   216.3  916.17   225.6  913.77
   244.2  911.86   263.8  910.34   273.6  909.06     303  905.08   312.8  903.38
   322.6  901.07   324.9  900.75   332.4   899.7   342.2  900.37   348.9 901.348
     352   901.8   381.4  902.11   420.6  903.62   459.8  906.67   489.2   910.8
     499   912.4   508.8  915.64   518.6   921.1   606.8  979.62   655.8 1010.87
#Mann= 3 , 0 , 0
       0      .1       0   324.9    .045       0   348.9      .1       0
Bank Sta=324.9,348.9
XS Rating Curve= 0 ,0
Exp/Cntr=0.3,0.1

Type RM Length L Ch R = 1 ,21349   ,230.7,224.7,218
XS GIS Cut Line= 3
     1683152.848       719537.34     1682669.615      719715.503
     1682548.399      719814.787
#Sta/Elev= 30
       0  961.54    77.7  934.14    87.5   931.2   116.6  925.41   145.8  915.98
   174.9  908.24   194.4  901.51   204.1  899.48   213.8  899.88   242.9  903.15
   262.4  903.85   272.1  903.58   281.8  903.18   291.5  901.97   320.7  896.57
   330.4  895.48   342.8  894.95   349.8  894.88   364.8 895.525   369.3  895.98
     379   899.5   417.8  922.28   437.3  936.44   466.4  960.47   476.2  967.73
   485.9  973.67   495.6  977.48     564  996.79   622.8 1016.65   671.7 1034.73
#Mann= 3 , 0 , 0
       0      .1       0   342.8    .045       0   364.8      .1       0
Bank Sta=342.8,364.8
XS Rating Curve= 0 ,0
Exp/Cntr=0.3,0.1

Type RM Length L Ch R = 1 ,21124.3 ,167.2,164.6,161.3
XS GIS Cut Line= 2
     1682985.577       719269.69     1682465.233      719649.236
#Sta/Elev= 30
       0   957.8    19.5  946.89      39  936.75    58.6  926.04    87.8   911.1
    97.6  905.52   107.3  899.41   117.1  895.35   126.9  894.17   136.6  894.56
   195.2  898.66   204.9  898.99   253.7     899   302.5  896.18   331.8  893.64
   341.6  893.21   351.3  894.02   361.1  895.74   370.8  897.99   380.6  902.04
   390.3  908.01   419.6  928.21   439.1  941.02   458.6  952.62   468.4  957.96
   478.2  962.64   507.4  973.96   536.7  984.35   575.8  996.47   644.1 1015.41
#Mann= 3 , 0 , 0
       0      .1       0   331.8    .045       0   351.3      .1       0
Bank Sta=331.8,351.3
XS Rating Curve= 0 ,0
Exp/Cntr=0.3,0.1

Type RM Length L Ch R = 1 ,20959.7 ,279,275.3,269.8
XS GIS Cut Line= 2
     1682871.371      719104.256     1682389.474      719561.569
#Sta/Elev= 30
       0  970.65    29.3  954.03    58.6  938.87   146.6  897.87   156.3  894.07
   166.1  892.16   175.9  891.84   195.4  893.62   224.7  897.59     254     899
   273.6  898.09   293.1  895.56   312.6  892.23   322.4  891.83   332.2  892.88
   351.7  895.66     381  896.95   390.8  898.55   400.6  901.42   410.3   905.5
   429.9  915.11   449.4  926.12   478.7  944.64   498.3  955.92   517.8  965.91
   527.6  970.29   556.9  979.03   576.4   985.6   644.8 1005.23   664.4  1011.8
#Mann= 3 , 0 , 0
       0      .1       0   312.6    .045       0   332.2      .1       0
Bank Sta=312.6,332.2
XS Rating Curve= 0 ,0
Exp/Cntr=0.3,0.1

Type RM Length L Ch R = 1 ,20684.4 ,188.8,196.8,205.3
XS GIS Cut Line= 2
     1682683.375      718848.185     1682293.317      719342.208
#Sta/Elev= 30
       0 1005.87    88.5  964.49   127.9  947.44   147.5  939.23   167.2  931.69
     177  927.35   226.2  909.32     236  905.49   245.9  900.26   255.7  893.94
   265.6  889.35   275.4  889.14   324.6  892.89   334.4   893.4   344.2   892.7
   357.1 890.723   363.9  889.53   373.7  889.05   384.1 889.274   413.1  891.04
   422.9  892.43   442.6  896.53   462.2  901.95   472.1  905.21   511.4  919.35
   540.9  930.73   550.8  935.08   590.1   955.6   609.8  966.45   629.4  975.48
#Mann= 3 , 0 , 0
       0      .1       0   357.1    .045       0   384.1      .1       0
Bank Sta=357.1,384.1
XS Rating Curve= 0 ,0
Exp/Cntr=0.3,0.1

Type RM Length L Ch R = 1 ,20487.6 ,329.1,314,298.5
XS GIS Cut Line= 2
     1682615.817      718791.468     1682155.541      719106.688
#Sta/Elev= 30
       0 1009.57    97.9  968.17   117.4  959.01   166.4  938.35   195.7  925.12
   225.1  912.56   244.7  903.61   254.5  899.94   264.2  897.26   283.8  892.93
   293.6  890.14   303.1 889.142   313.2     889     323     889   327.1  889.52
   342.6     892   352.3  892.89   362.1     893   371.9   893.8   391.5  892.55
   401.3   892.4   411.1  893.82     460  908.46   479.6  915.57   499.2  923.98
   518.7  933.08   528.5  937.88   538.3  943.28   548.1  947.99   557.9  951.49
#Mann= 3 , 0 , 0
       0      .1       0   303.1    .045       0   327.1      .1       0
Bank Sta=303.1,327.1
XS Rating Curve= 0 ,0
Exp/Cntr=0.3,0.1

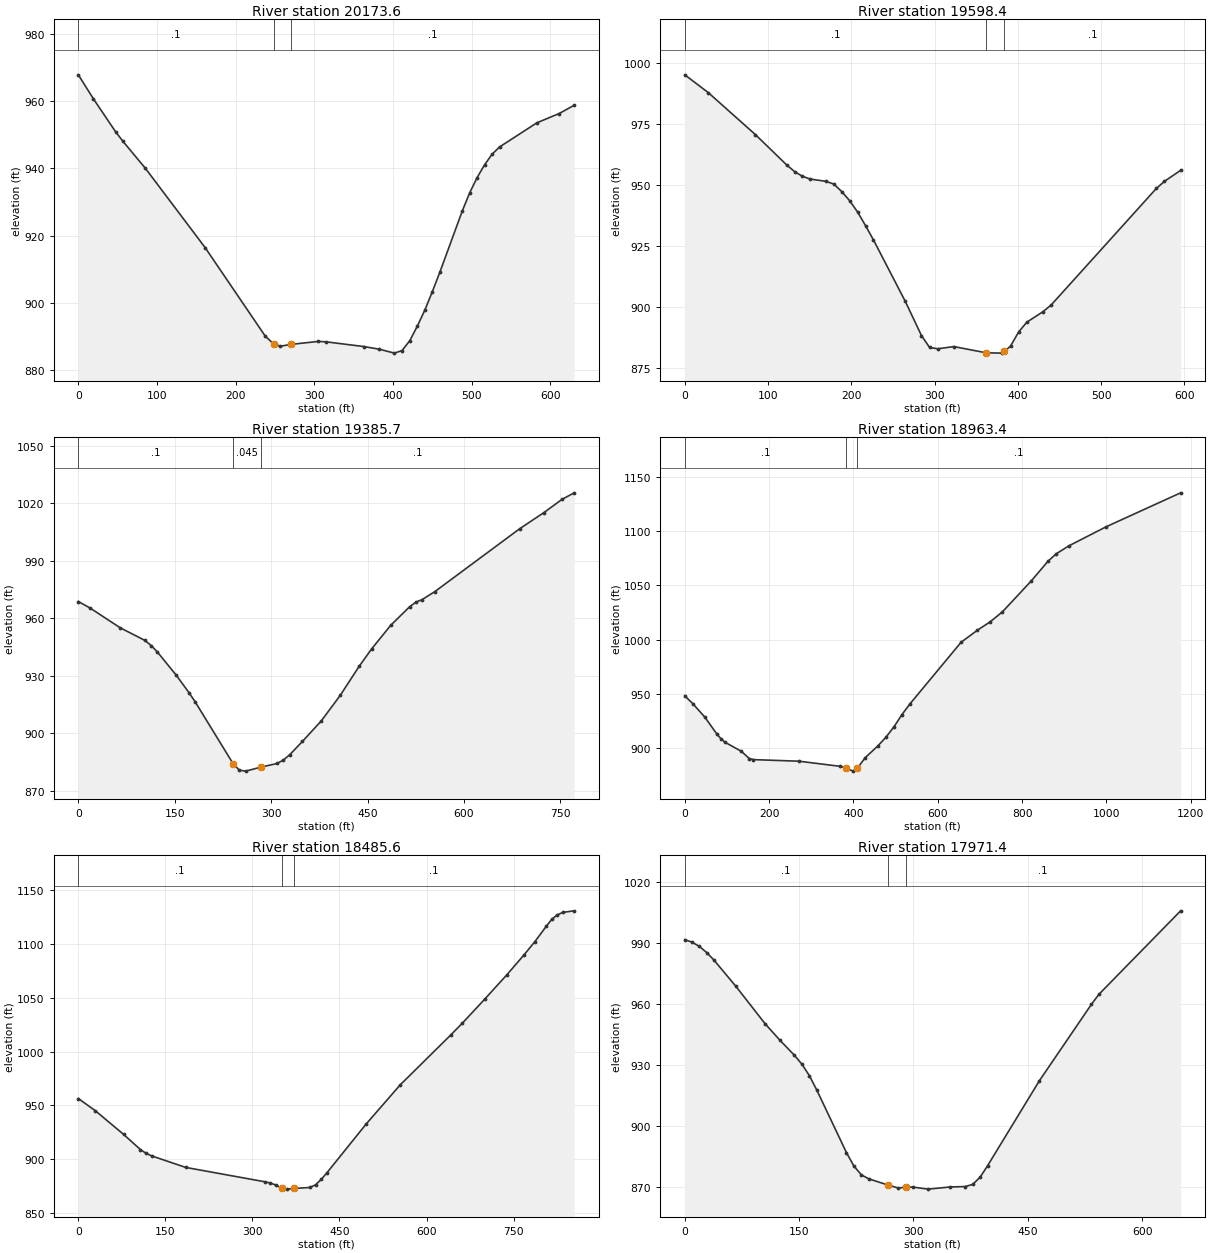
Type RM Length L Ch R = 1 ,20173.6 ,599.1,575.2,547.2
XS GIS Cut Line= 4
     1682276.553      718528.247     1682158.982      718712.128
     1682092.503      718924.424     1682089.053      719114.184
#Sta/Elev= 30
       0  967.84      19  960.76    47.4  950.89    56.9  948.01    85.4  939.98
   161.3   916.4   237.6  890.11   248.3  887.75   256.9  887.07     270 887.608
   305.3  888.51     315  888.38   363.3  886.97   382.7  886.19     402  885.02
   411.7   885.8   421.4   888.7     431  893.01   440.7  897.87   450.2  903.34
   459.7  909.09   488.2   927.3   497.6  932.69   507.1  937.26   516.6  941.07
   526.1   944.2   535.6  946.37   583.1  953.56   611.5  956.33   630.5  958.79
#Mann= 3 , 0 , 0
       0      .1       0   248.3    .045       0     270      .1       0
Bank Sta=248.3,270
XS Rating Curve= 0 ,0
Exp/Cntr=0.3,0.1

Type RM Length L Ch R = 1 ,19598.4 ,211.9,212.7,213.9
XS GIS Cut Line= 4
     1681656.554      718693.006     1681683.637      718860.367
     1681735.166      718928.634      1681973.73      719171.688
#Sta/Elev= 30
       0  995.13    28.3  987.81    84.8  970.63   122.4  958.19   131.9  955.45
   141.3  953.55   150.7   952.4   169.5  951.47     179  950.36   188.6  947.26
     198  943.54   207.6  938.89   217.1  933.31   226.6  927.47   264.8  902.31
   284.3  888.25     294   883.4   303.7  882.83   323.2  883.73   362.1  881.18
   381.6  881.05   383.9  881.74   391.3  883.95     401  889.71   410.8  893.72
   430.2  898.02     440  900.75   566.4  948.54   576.2  951.48   595.6  955.98
#Mann= 3 , 0 , 0
       0      .1       0   362.1    .045       0   383.9      .1       0
Bank Sta=362.1,383.9
XS Rating Curve= 0 ,0
Exp/Cntr=0.3,0.1

Type RM Length L Ch R = 1 ,19385.7 ,408.4,422.3,435.7
XS GIS Cut Line= 4
     1681486.134      718897.892     1681541.741      718960.639
     1681860.426       719320.24     1682020.534      719451.684
#Sta/Elev= 30
       0  968.72    18.6  965.24    65.2  954.98   103.4  948.44   113.3  945.74
   123.1  942.32   152.5  930.16   172.1  921.17   181.9  916.26   240.7  884.08
   250.5  880.63   260.4  880.13   284.1 882.216   309.4  884.13   319.2  885.95
     329  888.72   348.6  895.62     378  906.34   407.4  919.64   436.9  934.84
   456.5  944.02   485.9  956.23   515.3  965.92   525.1  968.34   534.9  969.72
   554.5  973.83   686.7 1006.72   724.4 1015.15   752.6 1022.06   771.5 1025.48
#Mann= 3 , 0 , 0
       0      .1       0   240.7    .045       0   284.1      .1       0
Bank Sta=240.7,284.1
XS Rating Curve= 0 ,0
Exp/Cntr=0.3,0.1

Type RM Length L Ch R = 1 ,18963.4 ,446.1,477.8,509
XS GIS Cut Line= 5
     1681393.982      718935.065     1681288.633      719045.891
     1681329.845      719377.296     1681234.259      719527.079
     1680843.634       719856.94
#Sta/Elev= 30
       0  948.17    19.1  940.95    47.8  928.42    76.4  912.74      86  908.59
    95.6  905.31   133.8  897.12   152.9  890.41   162.7  889.38   270.8  887.92
     369  883.16     383 881.653   398.5  878.77   409.4 881.489   427.9   891.2
   457.4  901.85     477  910.04   496.2  919.72   514.9  930.83   533.6  940.62
   655.2  997.56     694 1008.72   723.5 1016.21     753 1025.51   821.9 1054.24
   861.2 1072.23   880.8  1079.1   910.4 1086.38   998.8 1103.97  1175.8 1135.33
#Mann= 3 , 0 , 0
       0      .1       0     383    .045       0   409.4      .1       0
Bank Sta=383,409.4
XS Rating Curve= 0 ,0
Exp/Cntr=0.3,0.1

Type RM Length L Ch R = 1 ,18485.6 ,502.8,514.2,526.5
XS GIS Cut Line= 3
     1681380.224      718875.677     1680815.355      719058.673
     1680557.435      719096.353
#Sta/Elev= 30
       0  956.27    29.2     945    77.9  922.99   107.1   908.8   116.8  905.36
   126.5  902.93     185  892.25   321.2  878.92     331  877.77   340.7  875.71
   350.4  872.94   360.2  872.06   371.3  872.68   399.1  873.59   408.8  876.13
   418.6  881.12   428.3  887.22   496.4  932.88   554.8  969.08     642  1015.5
   661.4 1026.15     700 1048.53   738.6 1071.44   767.5 1089.54   786.8  1102.2
   806.2 1116.34   815.8 1122.87   825.5  1127.1   835.1  1129.4   854.4 1130.81
#Mann= 3 , 0 , 0
       0      .1       0   350.4    .045       0   371.3      .1       0
Bank Sta=350.4,371.3
XS Rating Curve= 0 ,0
Exp/Cntr=0.3,0.1

Type RM Length L Ch R = 1 ,17971.4 ,338.8,340.1,337.7
XS GIS Cut Line= 3
      1681435.84      718599.545     1681293.005      718616.962
     1680788.208      718573.375
#Sta/Elev= 30
       0  991.72     9.6  990.49    19.2  988.39    28.8  985.37    38.4  981.62
    67.2  968.67   105.5  950.25   124.7  942.24   143.9  934.74   153.6  930.42
   163.4  924.78   173.1  917.72   212.1  886.84   221.8  880.26   231.6  875.88
   241.3  873.91     266  870.92   280.3  869.35     290  869.87   299.8  869.81
   319.3  868.83   348.5   869.9     368   870.1   377.7  871.15   387.5   874.7
   397.2   880.3   465.4  922.31   533.6  959.89   543.4  964.81   650.6 1005.94
#Mann= 3 , 0 , 0
       0      .1       0     266    .045       0     290      .1       0
Bank Sta=266,290
XS Rating Curve= 0 ,0
Exp/Cntr=0.3,0.1

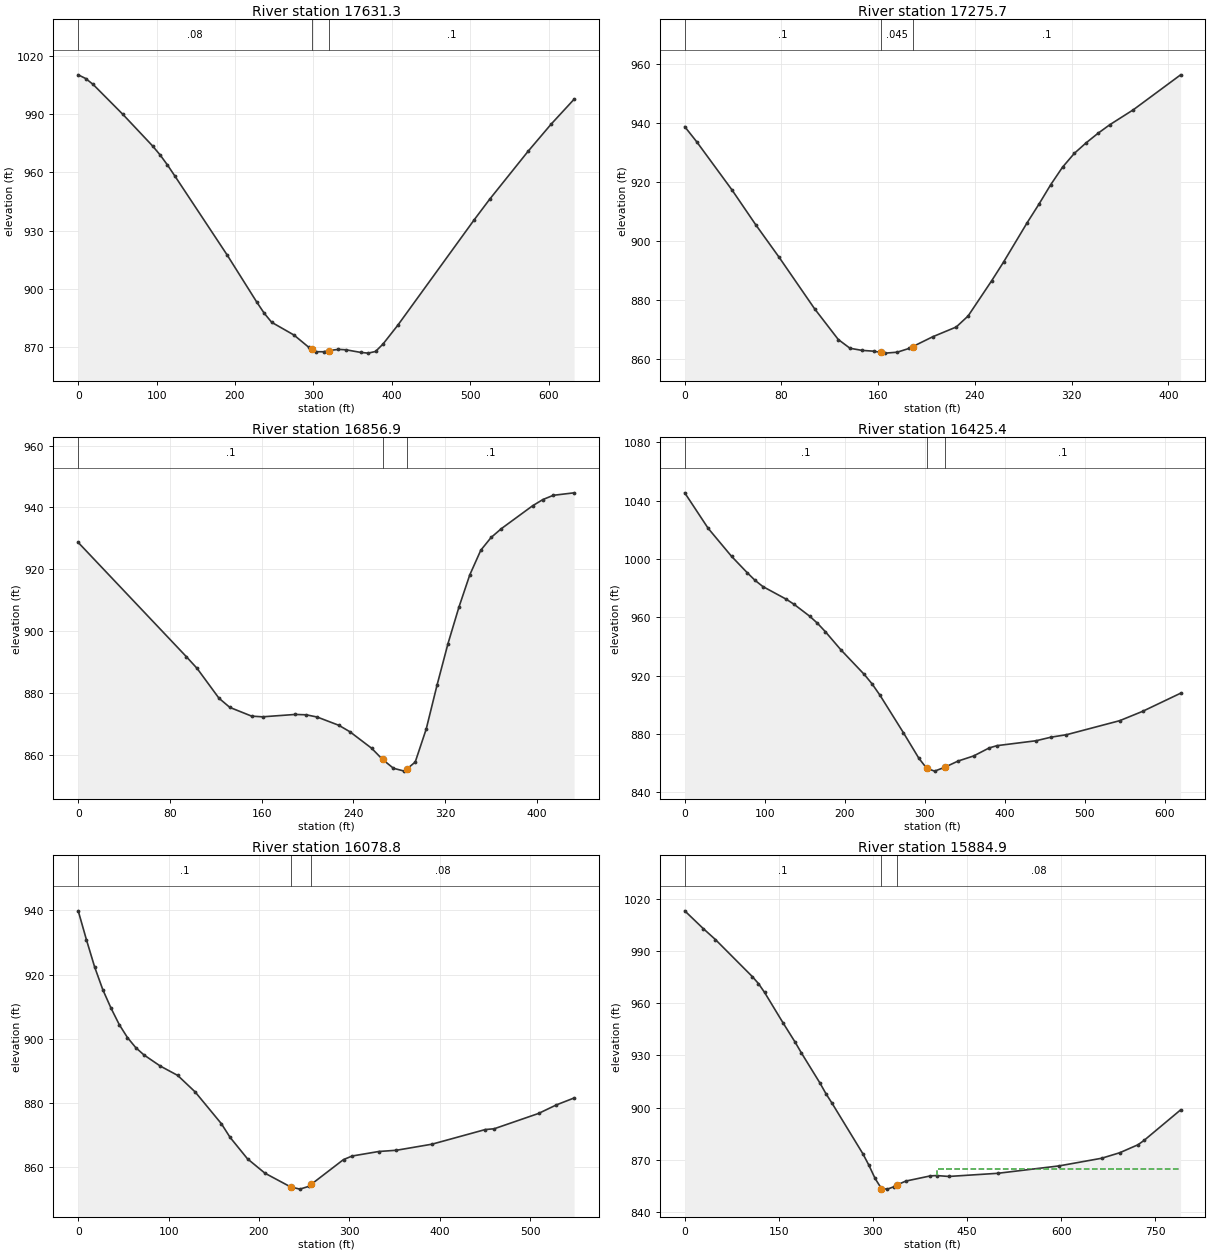
Type RM Length L Ch R = 1 ,17631.3 ,360.2,355.7,351.6
XS GIS Cut Line= 4
     1681489.861      718338.915     1681243.585      718322.417
     1681070.793      718272.651     1680864.861      718267.734
#Sta/Elev= 30
       0 1010.23     9.5 1008.34      19  1005.3      57  989.88    94.9  973.64
   104.4  969.07   113.9  963.83   123.4  958.13   189.9  917.62   227.8  893.32
   237.3  887.58   246.8  882.93   275.2  876.39   294.2  870.06   297.7  869.22
   303.6   867.8   313.1  867.77   319.7 868.381     332     869   341.5  868.79
   360.4  867.44   369.9  867.07   379.3  867.92   388.8  871.73   407.7  881.42
   505.1  935.62   524.7  946.13   573.8  970.84   603.2  984.81   632.6  997.67
#Mann= 3 , 0 , 0
       0     .08       0   297.7    .045       0   319.7      .1       0
Bank Sta=297.7,319.7
XS Rating Curve= 0 ,0
Exp/Cntr=0.3,0.1

Type RM Length L Ch R = 1 ,17275.7 ,404,418.7,432.6
XS GIS Cut Line= 2
      1681349.59      717981.348     1680939.442      717983.774
#Sta/Elev= 30
       0  938.81     9.8  933.74    39.1  917.35    58.6  905.63    78.1  894.51
   107.4  877.08     127  866.65   136.7  863.68   146.5  862.97   156.2  862.69
   162.2 862.288     166  862.03   175.8  862.35   185.6  863.63   188.7 864.263
   205.1  867.57   224.6  870.89   234.4  874.62   253.9  886.57   263.7  892.88
   283.2  906.21     293  912.53   302.7  919.11   312.5  925.06   322.3  929.77
     332  933.31   341.8  936.54   351.6  939.46   371.1  944.54   410.2  956.38
#Mann= 3 , 0 , 0
       0      .1       0   162.2    .045       0   188.7      .1       0
Bank Sta=162.2,188.7
XS Rating Curve= 0 ,0
Exp/Cntr=0.3,0.1

Type RM Length L Ch R = 1 ,16856.9 ,453.4,431.6,408.7
XS GIS Cut Line= 4
     1681428.752      717696.013     1681334.846      717703.678
     1681124.529      717556.092     1681044.203      717569.277
#Sta/Elev= 30
       0  928.67    94.2  891.75   103.7  887.91   122.8  878.25   132.3  875.27
   151.3  872.45   160.8  872.23   189.4     873   198.9  872.88   208.4  872.17
   227.4  869.48     237   867.4     256  862.05   265.5  858.43     275  855.58
   284.5  854.65   287.1  855.45     294  857.59   303.6  868.28   313.1  882.58
   322.6  895.94   332.1  907.69   341.6  918.17   351.2  926.15   360.2  930.28
   369.2  933.15   396.4  940.54   405.4  942.56   414.5  943.93   432.6  944.73
#Mann= 3 , 0 , 0
       0      .1       0   265.5    .045       0   287.1      .1       0
Bank Sta=265.5,287.1
XS Rating Curve= 0 ,0
Exp/Cntr=0.3,0.1

Type RM Length L Ch R = 1 ,16425.4 ,356,346.6,336.4
XS GIS Cut Line= 3
     1681661.276      717115.686     1681251.295      717272.581
     1681106.148      717379.995
#Sta/Elev= 30
       0 1045.38    29.3 1021.01    58.5 1001.81      78  990.63    87.8  985.38
    97.6   981.1   126.8  972.42   136.6  968.91   156.1  960.76   165.8  955.93
   175.6   950.2   195.1  937.69   224.4  920.77   234.1  914.31   243.9  906.58
   273.1  880.95   292.6  863.25   302.4  856.38   312.2  854.48   324.9 857.119
   341.4  861.37   360.9  864.87   380.4  870.39   390.2  871.96     439  875.32
     458  877.81     477  879.46   543.5  889.09     572  895.47   619.6  907.93
#Mann= 3 , 0 , 0
       0      .1       0   302.4    .045       0   324.9      .1       0
Bank Sta=302.4,324.9
XS Rating Curve= 0 ,0
Exp/Cntr=0.3,0.1

Type RM Length L Ch R = 1 ,16078.8 ,195.6,193.9,192.1
XS GIS Cut Line= 4
     1681310.349      716734.401     1681296.895      716824.233
     1681142.434      716983.586      1681086.39        717212.7
#Sta/Elev= 30
       0  939.88     9.1  930.88    18.2  922.38    27.2  915.34    36.3  909.59
    45.4  904.47    54.5  900.42    63.6  897.32    72.7  895.03    90.8  891.56
   110.1  888.64   129.4   883.5   158.4  873.61     168  869.37   187.3  862.68
   206.6  858.21   234.9  853.95   245.2  853.25   254.9  854.09   257.9 854.765
   293.5  862.45   303.1  863.56   332.4  864.96   352.1  865.35   391.4  867.24
   450.4   871.8   460.2  872.04   509.3  876.81     529  879.47   548.6  881.62
#Mann= 3 , 0 , 0
       0      .1       0   234.9    .045       0   257.9     .08       0
Bank Sta=234.9,257.9
XS Rating Curve= 0 ,0
Exp/Cntr=0.3,0.1

Type RM Length L Ch R = 1 ,15884.9 ,167.5,149.2,133.1
XS GIS Cut Line= 3
      1681250.22      716558.298     1680907.871       716973.78
     1680920.023      717225.516
#Sta/Elev= 30
       0 1013.03    29.4 1002.87    48.9  996.53   107.7  975.26   117.5  971.24
   127.2  966.19   156.6  948.72   176.2  937.45     186  931.37   215.3  914.25
   225.1  907.97   234.9  902.45   283.9   873.5   293.6  866.85   303.4  859.28
   313.6 853.457     323  853.16   332.8  854.45   339.1  855.71   352.4  857.78
   391.5  860.76   401.3  860.96   420.9  860.44   499.2  862.26   596.5  866.49
   664.4  870.89   693.4  874.07   722.5  878.66   732.2  881.17   790.4  898.69
#Mann= 3 , 0 , 0
       0      .1       0   313.6    .045       0   339.1     .08       0
#XS Ineff= 2 , 0
       0                   401.3       0     865
Permanent Ineff=
       F       F
Bank Sta=313.6,339.1
XS Rating Curve= 0 ,0
Exp/Cntr=0.3,0.1

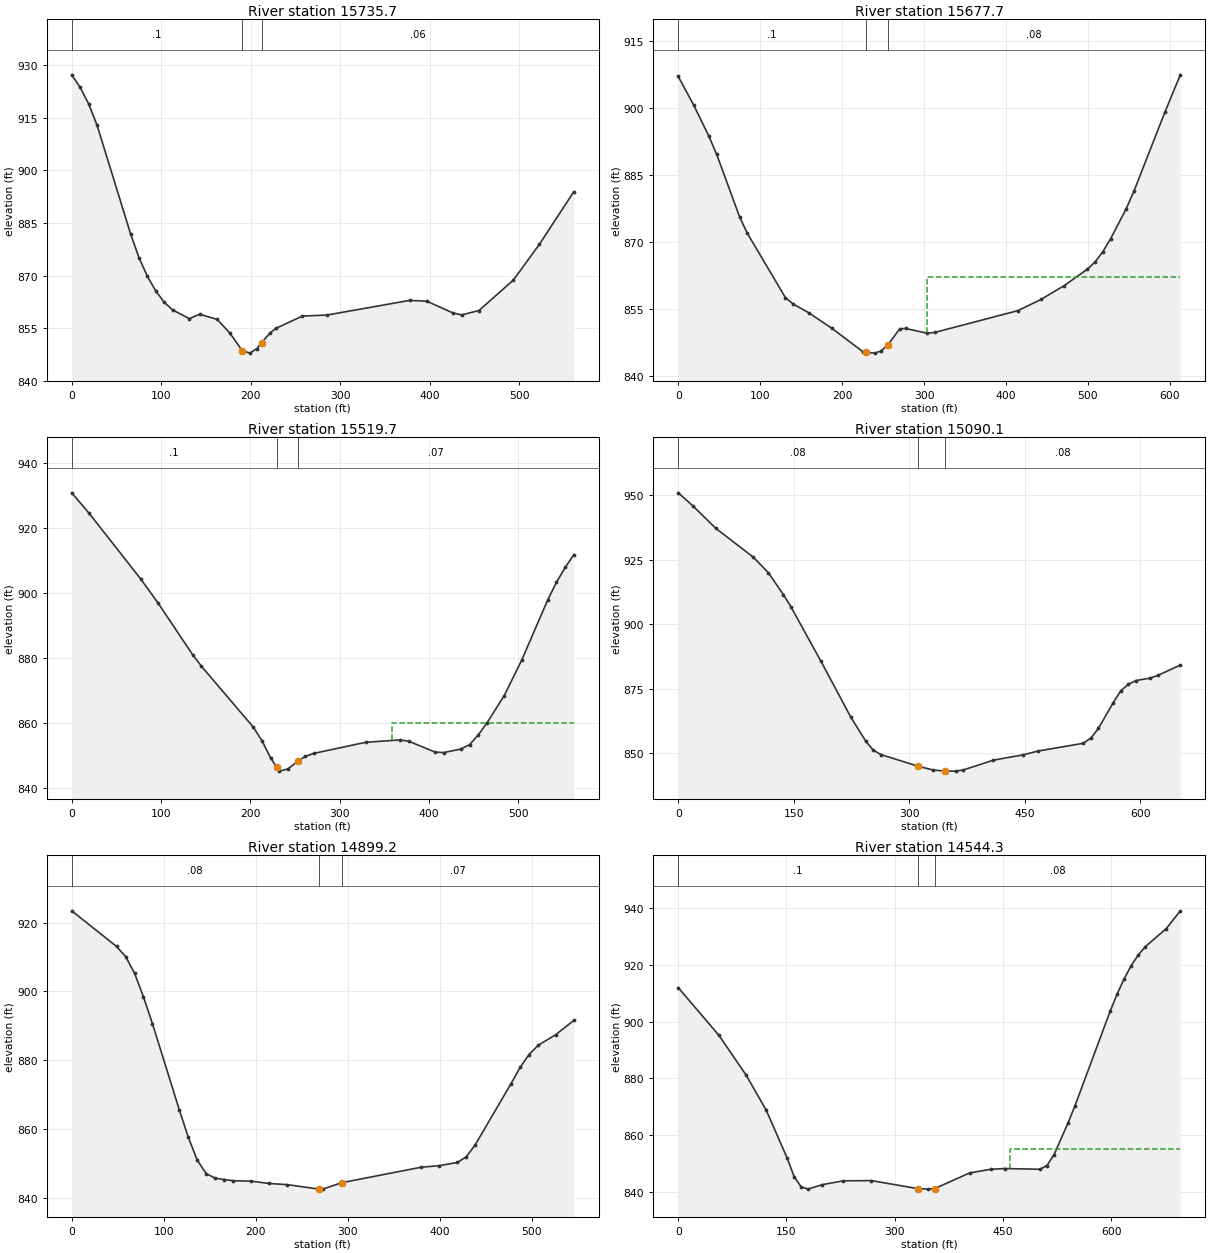
Type RM Length L Ch R = 1 ,15735.7 ,61.9,58,56.2
XS GIS Cut Line= 6
     1680917.085      716590.481      1680882.05      716717.131
     1680899.429      716734.771     1680905.724      716792.162
     1680866.425      716940.221     1680742.085      717087.704
#Sta/Elev= 30
       0  927.21     9.4   923.6    18.8  918.96    28.2  912.89    65.7  881.87
    75.1  875.07    84.5  869.75    93.9  865.56   103.2  862.41   112.6   860.2
   131.4   857.7   142.8  858.96   162.4   857.5   176.6  853.59   190.3  848.62
     199  847.88   206.8  849.19     212 850.832   221.4  853.62   228.4  854.98
   257.5  858.44   285.1  858.74   377.5  862.92   396.8  862.66   425.7  859.34
   435.4  858.77   454.7  860.01   493.2  868.69   522.2  878.85   560.8   893.9
#Mann= 3 , 0 , 0
       0      .1       0   190.3    .045       0     212     .06       0
Bank Sta=190.3,212
XS Rating Curve= 0 ,0
Exp/Cntr=0.3,0.1

Type RM Length L Ch R = 1 ,15677.7 ,143,158,168.1
XS GIS Cut Line= 6
     1680792.779       716554.37     1680780.715      716684.652
     1680842.339      716725.344     1680849.825      716803.082
     1680813.213      716937.443     1680688.613       717079.37
#Sta/Elev= 30
       0  907.06    18.7   900.7    37.4  893.67    46.7   889.7    74.8  875.62
    84.1  871.96   130.8  857.47   140.3  856.02   159.1  854.09   187.4   850.6
   225.4  845.33   229.1  845.18   239.6  845.02   247.3  845.47   256.1 846.936
   270.4  850.49   277.4  850.55   303.8  849.49   313.4  849.68   414.5  854.55
   442.7  857.06     471  860.16   499.4  863.86   508.8  865.49   518.3   867.8
   527.7   870.7   546.6  877.37     556  881.28   593.8  899.01   612.7  907.43
#Mann= 3 , 0 , 0
       0      .1       0   229.1    .045       0   256.1     .08       0
#XS Ineff= 2 , 0
       0                   303.8       0     862
Permanent Ineff=
       F       F
Bank Sta=229.1,256.1
XS Rating Curve= 0 ,0
Exp/Cntr=0.3,0.1

Type RM Length L Ch R = 1 ,15519.7 ,433.8,429.7,432.8
XS GIS Cut Line= 3
     1680789.698      716474.119     1680623.075      716907.913
     1680571.599      716990.612
#Sta/Elev= 30
       0  930.92    19.4  924.62    77.4  904.27    96.8  896.85   135.5  880.92
   145.2  877.41   203.3  858.62     213  854.42   222.7  849.09   229.4 846.314
   232.4  845.07     242  845.75   253.4 848.208   261.4  849.61   271.1  850.55
   329.2  853.97   367.9  854.71   377.6  854.26   406.6  850.96   416.3  850.79
   435.6  851.88   445.3  853.23     455  856.19   464.7  859.88   484.2  868.39
   503.7  879.28   532.9  897.91   542.6  903.29   552.4  907.89   562.1  911.86
#Mann= 3 , 0 , 0
       0      .1       0   229.4    .045       0   253.4     .07       0
#XS Ineff= 2 , 0
       0                   358.2       0     860
Permanent Ineff=
       F       F
Bank Sta=229.4,253.4
XS Rating Curve= 0 ,0
Exp/Cntr=0.3,0.1

Type RM Length L Ch R = 1 ,15090.1 ,191.1,190.9,181.5
XS GIS Cut Line= 3
     1680344.054      716265.505     1680273.421      716796.504
     1680184.019      716870.435
#Sta/Elev= 30
       0  950.84    19.5  945.64    48.7   937.1    97.4  925.91   116.9  919.92
   136.4  911.44   146.1  906.76     185  885.71     224  863.92   243.5  854.56
   253.2  851.12     263  849.43   311.3 844.893   331.2  843.41   345.8  843.03
   360.4     843   370.1  843.46   409.1  847.25     448  849.33   467.5  850.81
   525.9  853.79   535.7  855.84   545.3  859.52   564.7  869.55   574.4  874.12
     584  876.58   593.7  878.07     613  879.08   622.7  880.11   651.7  884.09
#Mann= 3 , 0 , 0
       0     .08       0   311.3    .045       0   345.8     .08       0
Bank Sta=311.3,345.8
XS Rating Curve= 0 ,0
Exp/Cntr=0.3,0.1

Type RM Length L Ch R = 1 ,14899.2 ,350.5,354.9,355.3
XS GIS Cut Line= 2
     1680157.016      716344.903     1680125.204       716889.58
#Sta/Elev= 30
       0  923.41    48.7  913.06    58.5  910.14    68.2  905.31    77.9  898.45
    87.7  890.64   116.9  865.64   126.7  857.63   136.4  851.04   146.1  847.14
   155.9  845.81   165.6  845.42   175.4  845.08   194.9  844.96   214.4  844.28
   233.8  843.95   268.3 842.664   272.8  842.64   293.3 844.504     380  849.01
   399.5  849.45     419  850.38   428.7  852.01   438.4  855.49   477.4  873.27
   487.2  877.96   496.9  881.68   506.6  884.33   526.1  887.51   545.6  891.61
#Mann= 3 , 0 , 0
       0     .08       0   268.3    .045       0   293.3     .07       0
Bank Sta=268.3,293.3
XS Rating Curve= 0 ,0
Exp/Cntr=0.3,0.1

Type RM Length L Ch R = 1 ,14544.3 ,484.2,501.8,516.6
XS GIS Cut Line= 3
     1679932.717      716311.841      1679870.94      716427.887
     1679748.511      716978.808
#Sta/Elev= 30
       0     912    56.3  895.21    93.9  881.26   122.1  868.74   150.9  851.95
   160.7  845.38   170.4  841.76   180.1  841.05   199.6  842.57   228.8  843.93
   267.7     844   332.3  841.17   345.5     841   355.3  841.17   403.9  846.71
   433.1  847.99   452.6  848.25   501.2     848     511  849.31   520.7  853.08
   540.1  864.26   549.9  870.42   598.5  903.64   608.2  909.71     618   915.1
   627.7  919.73   637.4  923.46   647.2   926.4   676.4   932.8   695.8  939.05
#Mann= 3 , 0 , 0
       0      .1       0   332.3    .045       0   355.3     .08       0
#XS Ineff= 2 , 0
       0                     460       0     855
Permanent Ineff=
       F       F
Bank Sta=332.3,355.3
XS Rating Curve= 0 ,0
Exp/Cntr=0.3,0.1