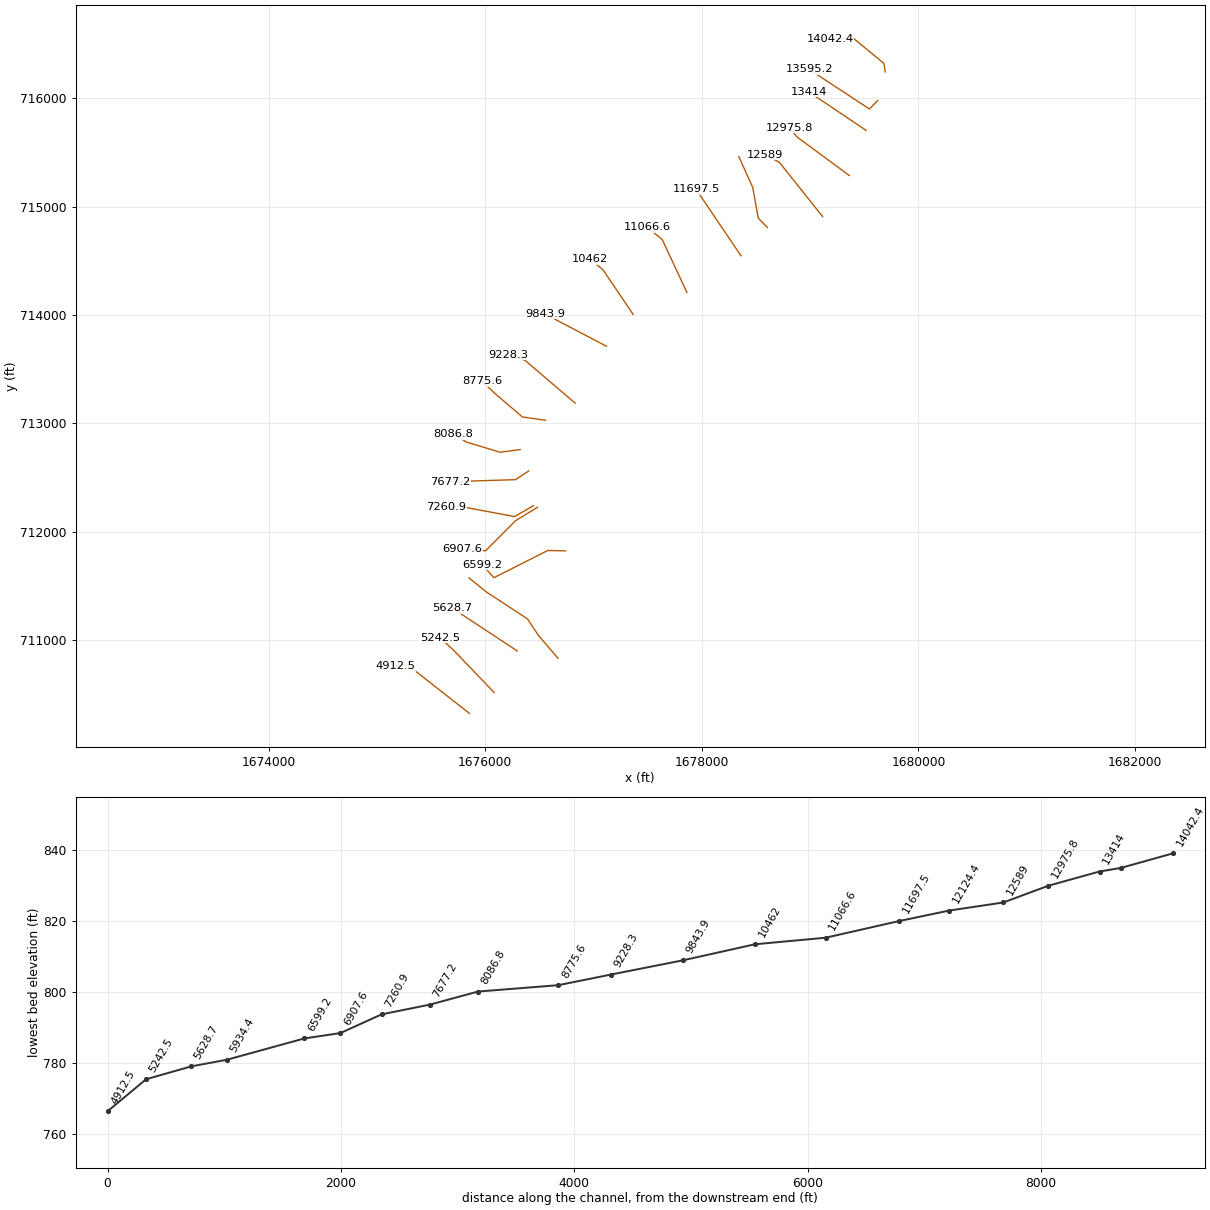
HEC-RAS study NFKINGSCK.prj: NFKINGSCK

--- NFKINGSCK.g09 (geometry) --- (continued)

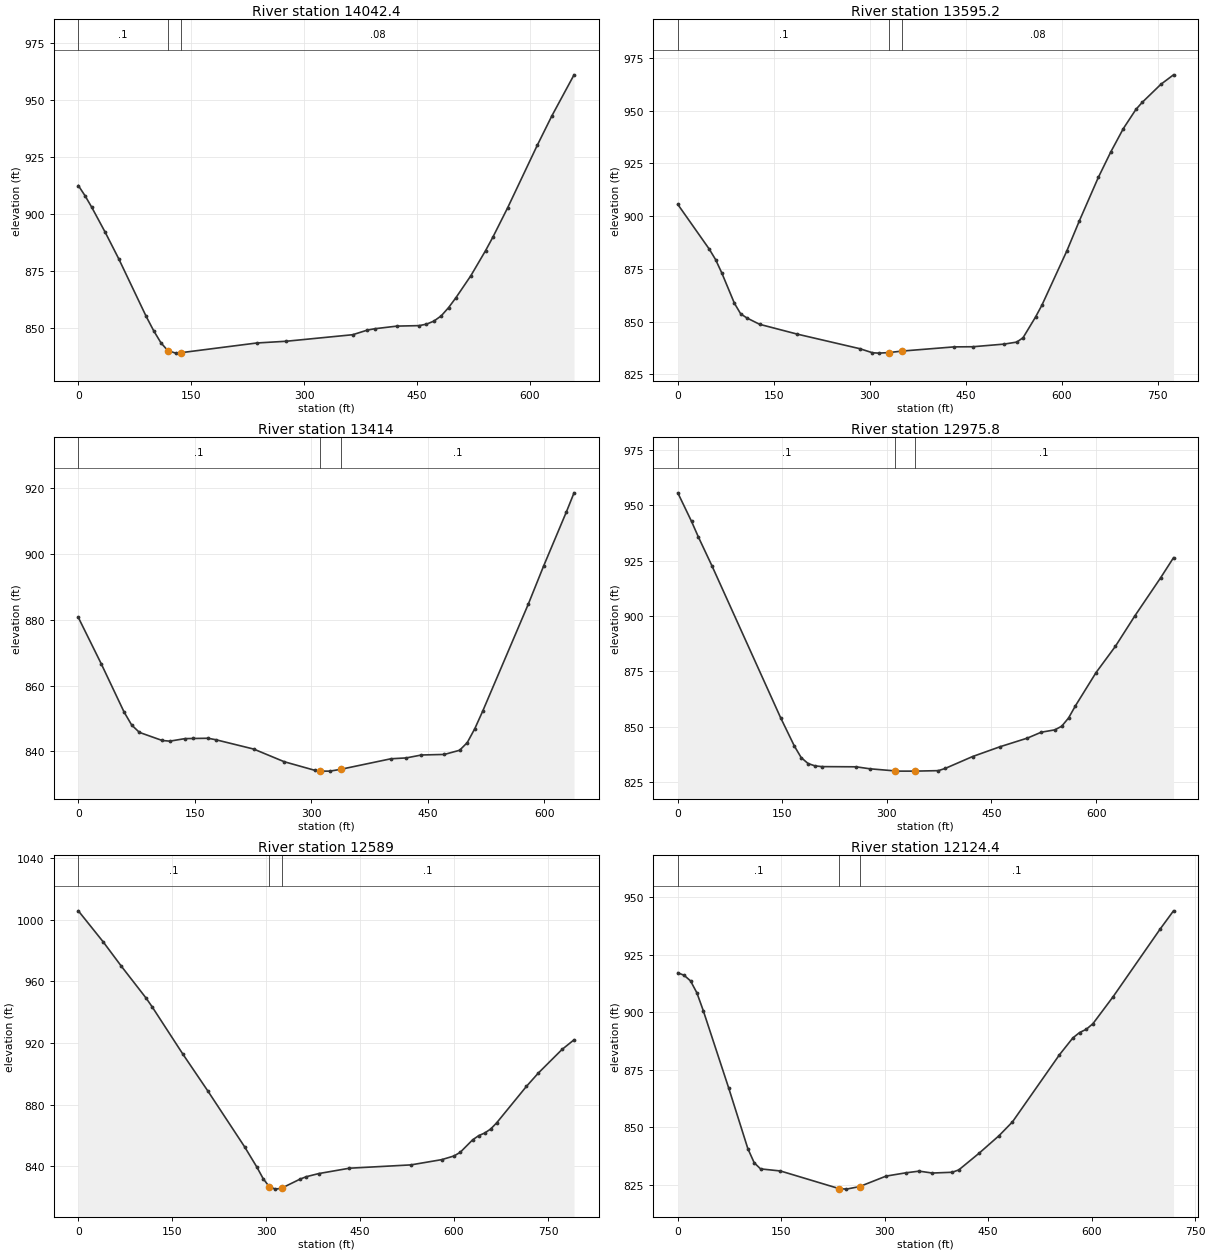
Type RM Length L Ch R = 1 ,14042.4 ,444.8,447.2,449.3
XS GIS Cut Line= 4
     1679693.394      716242.397     1679680.233      716321.653
     1679399.905      716551.942      1679184.28      716549.689
#Sta/Elev= 30
       0  912.46     8.9  908.01    17.8  902.97    35.7  892.01    53.6  880.46
    90.2  855.16     100  848.99   109.8  843.62   118.9 840.212   129.4   839.1
   136.9  839.31   237.2  843.54   276.4   844.3   364.7  847.16   384.3   849.2
   394.1  849.78   423.5  850.93   452.9  851.14   462.7  851.78   472.5  853.11
   482.3  855.42   492.1  859.04   501.9   863.4   521.6  872.96   541.2  883.96
     551  889.92   570.6  902.75   609.8  929.99   629.4     943   658.8  960.92
#Mann= 3 , 0 , 0
       0      .1       0   118.9    .045       0   136.9     .08       0
Bank Sta=118.9,136.9
XS Rating Curve= 0 ,0
Exp/Cntr=0.3,0.1

Type RM Length L Ch R = 1 ,13595.2 ,181.4,181.3,181
XS GIS Cut Line= 3
     1679623.283      715977.457      1679547.18      715900.591
     1678989.871      716265.916
#Sta/Elev= 30
       0  905.58    49.2  884.34      59  879.41    68.8  873.01    88.5  858.63
    98.3  853.62   108.2  851.65   127.8  848.68   186.6  844.02   284.6  837.09
   304.2  835.17     314     835     330 835.264   350.5 835.981   431.6  837.96
     461  838.03     510  839.29   529.6  840.24   539.4   842.3     559  852.17
   568.8   857.7     608  883.62   627.6  897.92     657  918.36   676.5  930.47
   696.1  941.55   715.7  950.62   725.5  953.96   754.9   962.6   774.5  967.06
#Mann= 3 , 0 , 0
       0      .1       0     330    .045       0   350.5     .08       0
Bank Sta=330,350.5
XS Rating Curve= 0 ,0
Exp/Cntr=0.3,0.1

Type RM Length L Ch R = 1 ,13414   ,440.4,438.2,435.5
XS GIS Cut Line= 2
     1679517.296      715702.511      1678987.49      716058.289
#Sta/Elev= 30
       0  880.75    29.4   866.7    58.9  851.98    68.7  848.02    78.6  845.79
     108  843.32   117.8  843.12   137.4  843.89   147.3  843.93   166.9     844
   176.7  843.57   225.8  840.71   265.1  836.86   304.4  834.25   310.7 834.086
   314.2     834     324     834   337.7 834.547   402.5  837.76   422.2  838.02
   441.8  838.91   471.3  839.08   490.9  840.35   500.7  842.67   510.5  846.95
   520.4  852.14   579.3   884.8   598.9  896.32   628.4  912.89   638.2  918.66
#Mann= 3 , 0 , 0
       0      .1       0   310.7    .045       0   337.7      .1       0
Bank Sta=310.7,337.7
XS Rating Curve= 0 ,0
Exp/Cntr=0.3,0.1

Type RM Length L Ch R = 1 ,12975.8 ,391.4,386.8,382.5
XS GIS Cut Line= 3
     1679361.187      715286.681     1678878.073      715642.477
     1678808.489      715729.093
#Sta/Elev= 30
       0  955.69    19.7  942.79    29.5  935.76    49.2  922.58   147.5  854.12
   167.2  841.34     177  836.11   186.9  833.43   196.7  832.38   206.6  832.04
   255.7  831.95   275.4  831.06   311.2  830.11   314.8     830   340.2     830
   373.8  830.22   383.6  831.22   422.9  836.59   462.3  841.02   501.6  844.93
   521.3  847.57     541  848.65   550.8  850.31   560.6  854.03   570.5  859.55
     600  874.52   627.8   886.4   655.5  900.05   692.6  917.31   711.1  926.39
#Mann= 3 , 0 , 0
       0      .1       0   311.2    .045       0   340.2      .1       0
Bank Sta=311.2,340.2
XS Rating Curve= 0 ,0
Exp/Cntr=0.3,0.1

Type RM Length L Ch R = 1 ,12589   ,475.4,464.6,452.8
XS GIS Cut Line= 3
      1679114.65      714907.678     1678716.131      715407.638
     1678581.927      715479.527
#Sta/Elev= 30
       0 1005.72    39.4  985.76    68.8  969.76   108.2  949.15     118  943.41
   167.2  912.66   206.6  889.05   265.6  852.67   285.2   839.5   295.1  832.12
   304.9  826.85   314.8  825.28   324.6  825.89   354.1  831.77   363.9  833.32
   383.6  835.34   432.8  838.84   531.2     841   580.3   844.4     600  846.79
   609.8  849.14   629.5  857.18   639.4  859.97   648.9  861.65   658.4  864.24
   667.9  868.19   715.5  891.86   734.5  900.51   772.6  915.91   791.6  922.09
#Mann= 3 , 0 , 0
       0      .1       0   304.9    .045       0   324.6      .1       0
Bank Sta=304.9,324.6
XS Rating Curve= 0 ,0
Exp/Cntr=0.3,0.1

Type RM Length L Ch R = 1 ,12124.4 ,416.9,426.9,436.3
XS GIS Cut Line= 4
     1678604.891      714807.657     1678520.983      714893.491
     1678469.879       715176.22      1678341.87      715460.001
#Sta/Elev= 30
       0  917.15     9.2  916.05    18.5   913.6    27.7   908.4    36.9  900.71
    73.9  866.91   101.6  840.59   110.8  834.46     120  831.81   148.8   830.9
   233.5 823.255   244.5     823   263.5 824.103     302  828.67   330.7   830.1
   349.9  830.83     369     830   397.8  830.34   407.3  831.35   436.5  838.54
   465.7  846.25   485.2  852.26   553.3  881.46   572.7  888.78   582.5  891.14
   592.2  892.55   601.9  895.01   631.1  906.72   699.2  936.13   718.7  944.11
#Mann= 3 , 0 , 0
       0      .1       0   233.5    .045       0   263.5      .1       0
Bank Sta=233.5,263.5
XS Rating Curve= 0 ,0
Exp/Cntr=0.3,0.1

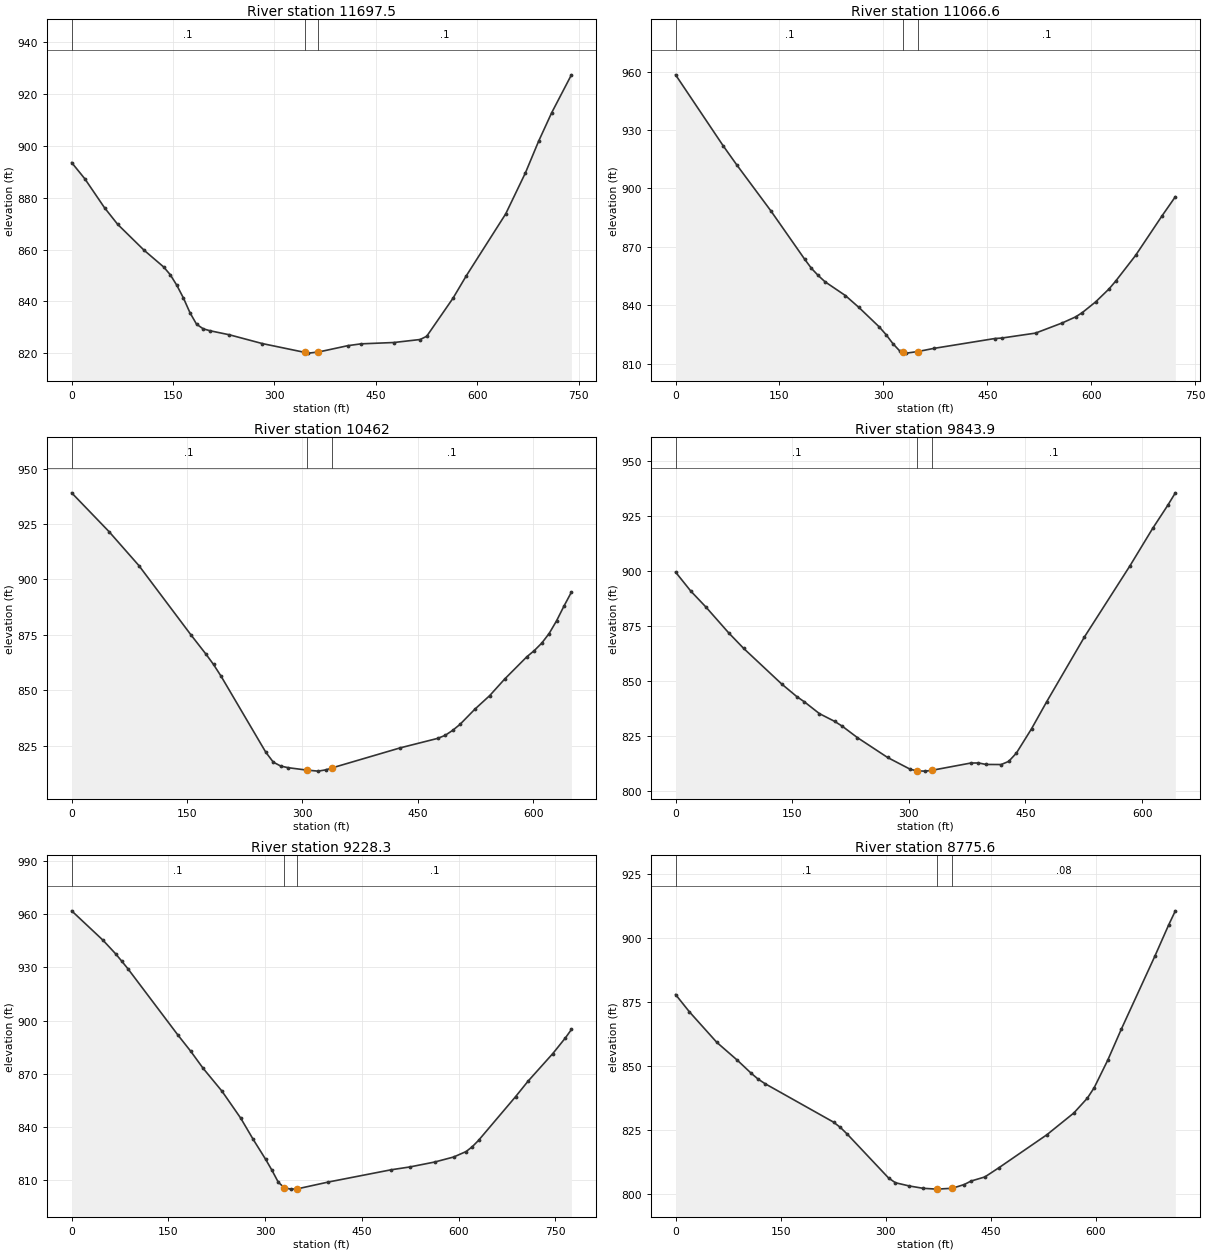
Type RM Length L Ch R = 1 ,11697.5 ,634.4,630.9,626.2
XS GIS Cut Line= 2
     1678361.684      714545.676      1677947.62      715158.207
#Sta/Elev= 30
       0  893.62    19.5  887.35    48.6  876.19    68.1  869.77     107  859.82
   136.2   853.3   145.9  850.32   155.6  846.24   165.4  841.32   175.1  835.63
   184.8  831.21   194.6  829.46   204.3  828.72   233.5  827.13   282.1  823.75
   344.8 820.354   350.2  820.06   364.8  820.47   408.6  822.94     428  823.64
   476.7  824.16   515.6  825.32   525.3  826.57   564.2  841.26   583.7  849.84
   642.1  873.78   671.3  889.62   690.7  901.76   710.2  912.86   739.4  927.48
#Mann= 3 , 0 , 0
       0      .1       0   344.8    .045       0   364.8      .1       0
Bank Sta=344.8,364.8
XS Rating Curve= 0 ,0
Exp/Cntr=0.3,0.1

Type RM Length L Ch R = 1 ,11066.6 ,600.6,604.6,607.8
XS GIS Cut Line= 3
     1677862.562      714207.126     1677634.521      714695.754
      1677492.94      714810.586
#Sta/Elev= 30
       0  958.32    68.6  921.92    88.2  912.12   137.3  888.57   186.3  863.63
   196.1  858.93   205.9  855.24   215.7  852.03   245.1  844.95   264.7  838.82
   294.1   828.8   303.9  824.85   313.7  820.24   323.5  816.52     329 815.868
   333.3  815.36     350 816.186   372.6  817.78   460.8  822.86   470.6  823.09
   519.6  825.64   558.4   830.9   577.6  833.99   587.2  836.19   606.4  841.68
   625.6  848.29   635.2  852.29     664  865.52   702.3   885.9   721.5  895.71
#Mann= 3 , 0 , 0
       0      .1       0     329    .045       0     350      .1       0
Bank Sta=329,350
XS Rating Curve= 0 ,0
Exp/Cntr=0.3,0.1

Type RM Length L Ch R = 1 ,10462   ,605.3,618,628.5
XS GIS Cut Line= 3
      1677365.56      714005.938      1677087.98      714415.914
     1676969.995      714515.635
#Sta/Elev= 30
       0  939.08    48.5  921.61    87.4  906.26   155.3  874.88   174.7  866.25
   184.4  861.64   194.2  856.35   252.4  822.02   262.1  817.57   271.8   815.8
   281.5  815.07   305.5 813.986   320.4  813.52   330.1  814.08   338.5 814.981
   427.2  824.03   475.7  828.29   485.4  829.65   495.1  831.88   504.8  834.62
   524.1  841.47   543.4   847.6   562.7  855.02   591.7  865.13   601.3  867.89
     611  871.27   620.6   875.6   630.3  881.35   639.9  887.98   649.6  894.28
#Mann= 3 , 0 , 0
       0      .1       0   305.5    .045       0   338.5      .1       0
Bank Sta=305.5,338.5
XS Rating Curve= 0 ,0
Exp/Cntr=0.3,0.1

Type RM Length L Ch R = 1 ,9843.9  ,620,615.7,609.9
XS GIS Cut Line= 2
     1677119.241      713711.773     1676550.024      714010.405
#Sta/Elev= 30
       0  899.58    19.5  890.96      39  883.69    68.2  871.97    87.6  864.84
   136.4  848.68   155.8  842.95   165.6  840.55     185  835.17   204.5  831.66
   214.3  829.47   233.7  824.29   272.7  815.21   301.9  809.83     311 809.096
   321.4     809     330 809.392   379.8  812.69   389.6  812.72   399.3  812.04
   418.8     812   428.5  813.45   438.3   817.2   457.8  828.26   477.2  840.52
   525.9  870.09   584.4  902.44   613.6  919.46   633.1  930.02   642.8  935.66
#Mann= 3 , 0 , 0
       0      .1       0     311    .045       0     330      .1       0
Bank Sta=311,330
XS Rating Curve= 0 ,0
Exp/Cntr=0.3,0.1

Type RM Length L Ch R = 1 ,9228.3  ,455.7,452.7,450.1
XS GIS Cut Line= 3
     1676831.971      713185.943     1676366.349      713582.788
     1676211.184      713633.786
#Sta/Elev= 30
       0  961.94    48.6  945.37      68  937.78    77.7  933.56    87.4  929.21
   165.1  891.75   184.5  882.83   203.9  873.13   233.1  860.26   262.2  845.03
   281.6  833.02     301  821.72   310.8  815.54   320.5  808.87     330 805.746
   339.9     805     350 805.159   398.2  809.01   495.3   815.9   524.4   817.5
   563.2   820.3   592.4  823.11   611.8   826.2   621.4  828.95     631  832.48
   688.6   857.2   707.9  865.91   746.3  881.48   765.5  890.17   775.1  895.02
#Mann= 3 , 0 , 0
       0      .1       0     330    .045       0     350      .1       0
Bank Sta=330,350
XS Rating Curve= 0 ,0
Exp/Cntr=0.3,0.1

Type RM Length L Ch R = 1 ,8775.6  ,675.4,688.9,698.4
XS GIS Cut Line= 4
     1676557.075      713028.881     1676343.628       713059.44
     1676104.525      713263.166     1675970.053      713388.039
#Sta/Elev= 30
       0  877.91    19.6   871.2    58.8  859.26    88.2  852.27   107.8  847.23
   117.6  844.96   127.4  843.18   225.4  828.14   235.3  826.04   245.1  823.43
     304  806.34   313.8  804.49   333.4  803.24     353  802.33   372.7     802
     373     802     395 802.334     412   803.8   421.8  805.16   441.4  806.75
     461  810.26   529.8  823.19   568.4   831.7   587.7  837.49   597.4  841.54
   616.7  852.25     636   864.3   684.3  893.03   703.6  904.97   713.3  910.56
#Mann= 3 , 0 , 0
       0      .1       0     373    .045       0     395     .08       0
Bank Sta=373,395
XS Rating Curve= 0 ,0
Exp/Cntr=0.3,0.1

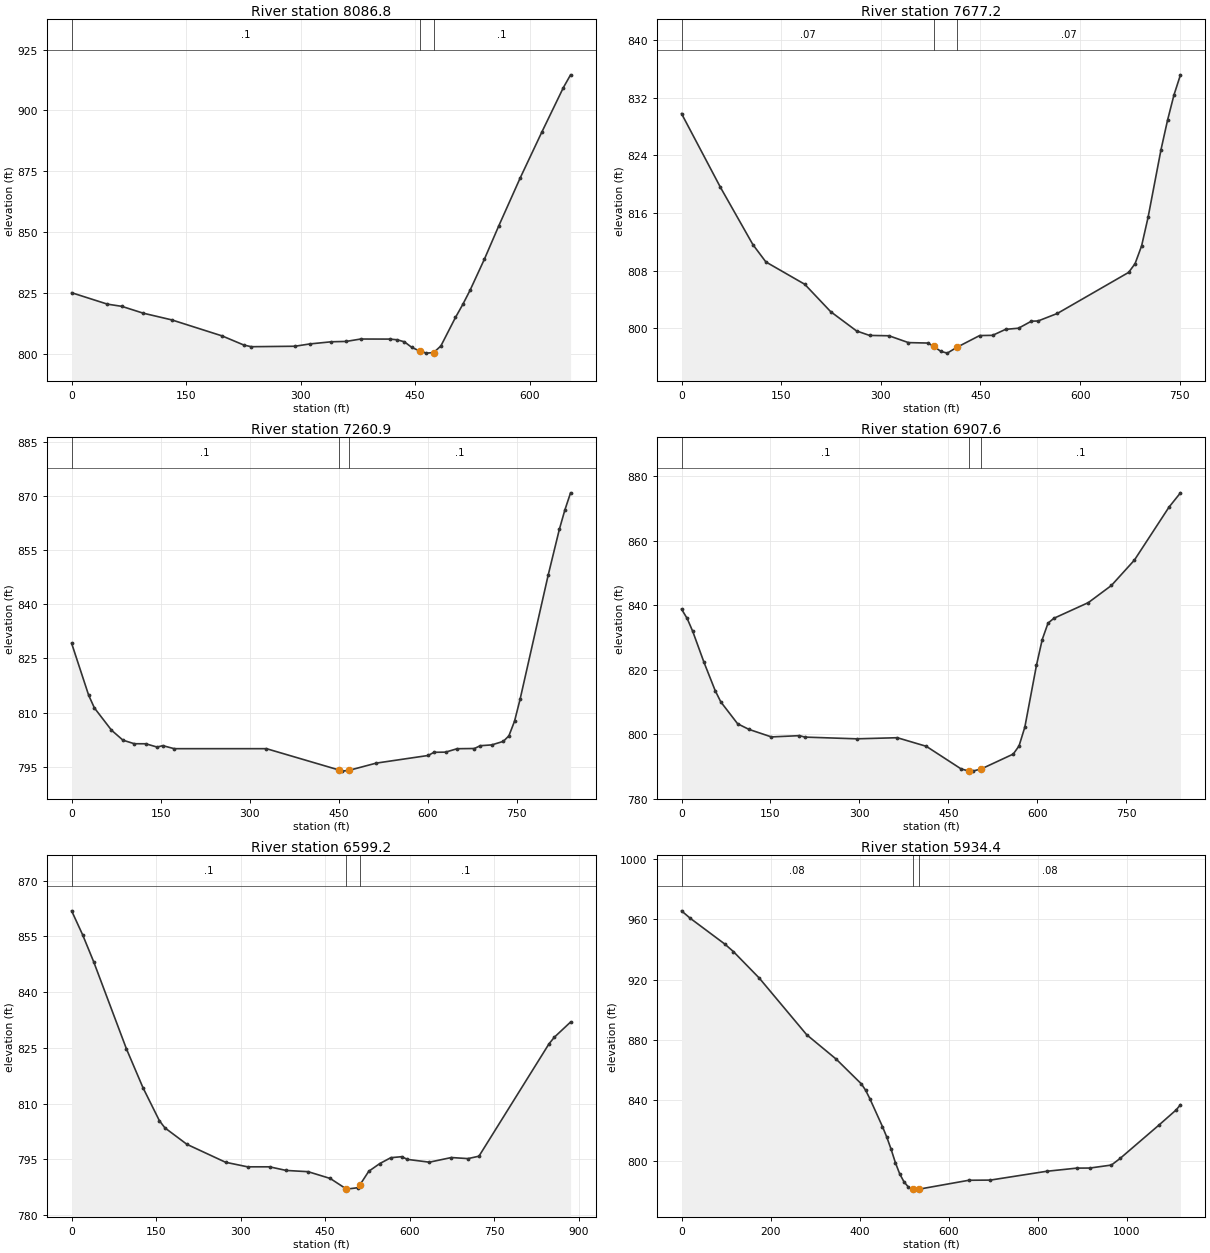
Type RM Length L Ch R = 1 ,8086.8  ,411.5,409.6,392.6
XS GIS Cut Line= 4
     1676323.252      712758.936     1676137.344       712733.85
     1675826.313      712828.151     1675706.065      712902.165
#Sta/Elev= 30
       0  825.04    46.9  820.34    65.7  819.44    93.8  816.63   131.3  813.86
   197.2  807.28   225.8  803.51   235.4  802.84   292.7  803.03   311.9  803.97
   340.5  804.87   359.7  805.01   378.8     806     417  805.97   426.6  805.69
   436.1  804.84   445.7  802.57     457 800.935   464.8   800.2   474.4  800.41
   483.9  803.17     503  814.88   512.6  820.24     522  825.99   540.8  838.77
   559.7  852.51   587.9   872.3   616.2  891.12   644.4   909.4   653.8  914.63
#Mann= 3 , 0 , 0
       0      .1       0     457    .045       0   474.4      .1       0
Bank Sta=457,474.4
XS Rating Curve= 0 ,0
Exp/Cntr=0.3,0.1

Type RM Length L Ch R = 1 ,7677.2  ,413.3,416.3,430.5
XS GIS Cut Line= 3
     1676402.388      712561.743      1676280.03      712481.106
     1675675.809      712461.996
#Sta/Elev= 30
       0   829.8    58.6  819.56   107.5   811.6     127   809.2   185.5   806.1
   224.5   802.3   263.5  799.62     283     799   312.3  798.95   341.6     798
   370.8  797.94   379.4 797.492   390.3  796.79     400  796.54   414.4 797.341
   448.8  798.98   468.3  799.01   487.8  799.84   507.3     800   526.8  800.98
   536.6     801   565.8  802.05   673.1  807.75   682.8  808.97   692.6  811.43
   702.3  815.38   721.8  824.79   731.6  828.86   741.3  832.38   751.1  835.18
#Mann= 3 , 0 , 0
       0     .07       0   379.4    .045       0   414.4     .07       0
Bank Sta=379.4,414.4
XS Rating Curve= 0 ,0
Exp/Cntr=0.3,0.1

Type RM Length L Ch R = 1 ,7260.9  ,329.2,353.3,376.4
XS GIS Cut Line= 4
     1676446.342      712241.075     1676271.444       712140.49
     1675754.534      712236.875     1675641.577      712227.993
#Sta/Elev= 30
       0  829.21    28.8  814.78    38.4  811.29    67.2  805.13    86.5  802.36
   105.7  801.37   124.9  801.36   144.1  800.45   153.7  800.84   172.9     800
   328.4     800   449.9  794.13   454.9  793.78   466.9  793.97   513.4     796
     601  798.12   610.7     799   630.2  799.04   649.7  799.99   678.9  800.05
   688.6  800.82   708.1  801.05   727.6  802.03     737  803.57   746.5  807.63
   755.9  813.75   803.1  848.04     822  860.78   831.4   866.2   840.9   870.9
#Mann= 3 , 0 , 0
       0      .1       0   449.9    .045       0   466.9      .1       0
Bank Sta=449.9,466.9
XS Rating Curve= 0 ,0
Exp/Cntr=0.3,0.1

Type RM Length L Ch R = 1 ,6907.6  ,316.7,308.5,300.1
XS GIS Cut Line= 4
     1676482.249      712225.632     1676280.162      712102.202
      1676003.99      711824.983     1675790.843      711838.913
#Sta/Elev= 30
       0  838.75     9.5  835.86    18.9  831.86    37.9  822.25    56.8  813.48
    66.3  809.97    94.7  803.19   113.7  801.46   151.6  799.12   198.9  799.51
   208.4  799.06   295.5  798.53     364  798.87   412.9  796.21   471.6   789.2
     485  788.53   491.2  788.51     506 789.219   559.6   793.8   569.4  796.33
   579.2  802.19   598.8  821.35   608.5  829.32   618.3   834.4   628.1   835.9
   686.4  840.78   725.2  846.08     764  853.95   822.3  870.36   841.7  874.81
#Mann= 3 , 0 , 0
       0      .1       0     485    .045       0     506      .1       0
Bank Sta=485,506
XS Rating Curve= 0 ,0
Exp/Cntr=0.3,0.1

Type RM Length L Ch R = 1 ,6599.2  ,687.9,664.7,640.3
XS GIS Cut Line= 4
     1676743.362      711823.984      1676577.84       711827.76
     1676080.265      711576.395     1675972.529      711698.116
#Sta/Elev= 30
       0  861.87    19.5  855.44      39  848.23    97.4   824.7   126.6  814.31
   155.8  805.41   165.6  803.48   204.7  799.05   273.2  794.23   312.3     793
   351.4     793   380.7  792.03   419.8  791.69     459  789.87     487 787.098
   488.3     787   507.9  787.38     512 788.211   527.4   791.8     547  793.88
   566.6  795.46   586.1  795.73   595.9     795     635  794.25   674.1   795.5
   703.5  795.21     723  795.86   847.3  826.08   856.9  827.88   885.6  831.95
#Mann= 3 , 0 , 0
       0      .1       0     487    .045       0     512      .1       0
Bank Sta=487,512
XS Rating Curve= 0 ,0
Exp/Cntr=0.3,0.1

Type RM Length L Ch R = 1 ,5934.4  ,305.7,305.8,305.4
XS GIS Cut Line= 5
     1676672.832       710832.99     1676489.774      711046.468
     1676390.789       711196.38     1676009.025      711446.228
     1675850.784       711574.31
#Sta/Elev= 30
       0  965.74    19.4  960.84      97  943.73   116.4  938.73   174.6  921.11
   281.2  883.47   347.4   867.3   404.1  850.81   413.6   846.6     423  841.05
   451.4  822.48   460.9  815.65   470.6  807.61   480.3  798.64     490  791.18
   499.7  785.84   509.4  782.45   519.1  781.13   528.8     781     534 781.005
   645.3  786.88   693.8     787     820  792.84     888  794.95   917.1     795
   965.6  796.98     985  801.34  1072.2  823.48    1111  833.57  1120.7  837.04
#Mann= 3 , 0 , 0
       0     .08       0   519.1    .045       0     534     .08       0
Bank Sta=519.1,534
XS Rating Curve= 0 ,0
Exp/Cntr=0.3,0.1

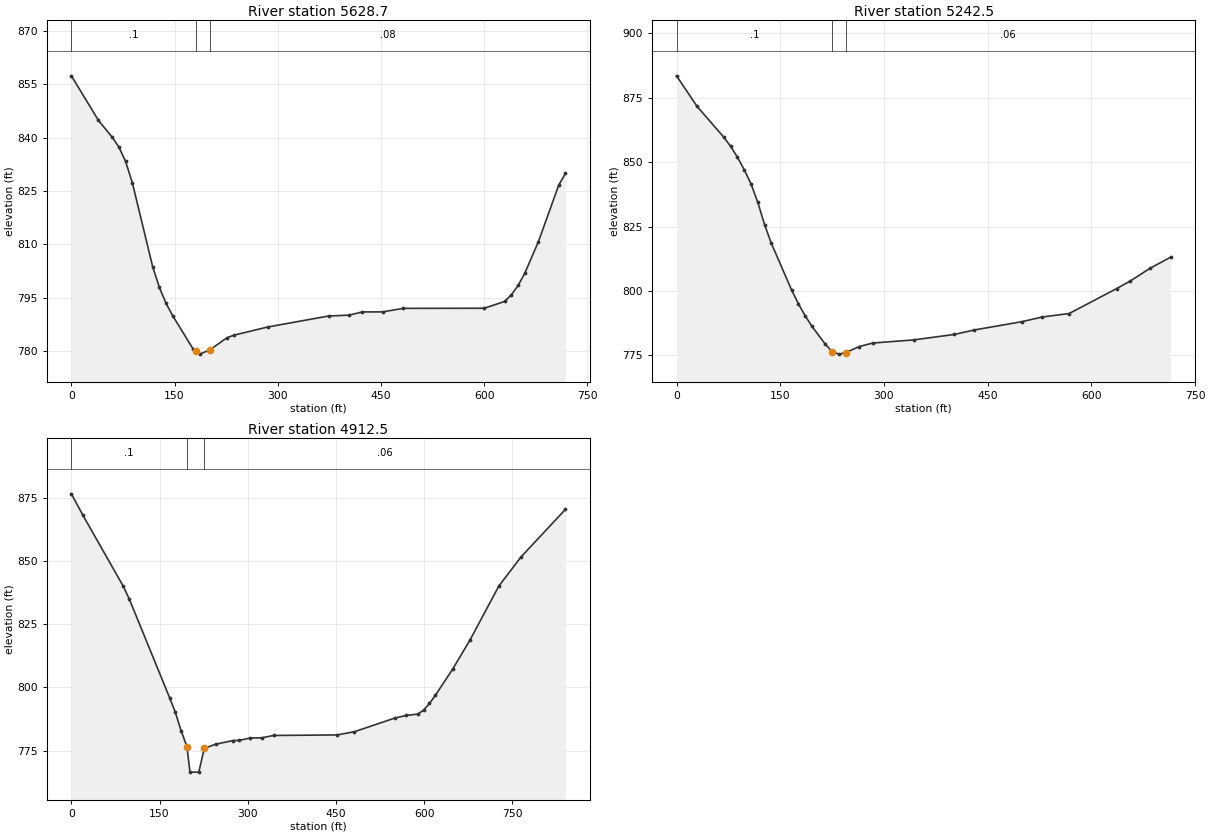
Type RM Length L Ch R = 1 ,5628.7  ,391.3,386.2,381
XS GIS Cut Line= 2
     1676296.079      710900.625     1675696.409      711295.886
#Sta/Elev= 30
       0  857.41    39.4  844.87      59  840.22    68.9  837.44    78.7  833.38
    88.6  827.36   118.1  803.77   127.9  797.91   137.7  793.38   147.6  789.83
   177.1  780.53   180.5  780.04   186.9  779.13   201.5 780.365   226.3  783.75
   236.1  784.45   285.3  786.76   373.9  789.85   403.4  790.09   423.1     791
   452.6  791.01   482.1     792   600.2  792.04   629.7  793.94   639.5   795.8
   649.4  798.45   659.2  801.94   678.9  810.77   708.4  826.66   718.2  829.97
#Mann= 3 , 0 , 0
       0      .1       0   180.5    .045       0   201.5     .08       0
Bank Sta=180.5,201.5
XS Rating Curve= 0 ,0
Exp/Cntr=0.3,0.1

Type RM Length L Ch R = 1 ,5242.5  ,326.7,330.1,333.4
XS GIS Cut Line= 3
     1676083.622      710516.217     1675710.869      710904.996
     1675581.769      711024.575
#Sta/Elev= 30
       0  883.56    29.4   871.8    68.6  859.66    78.3  856.17    88.1  851.94
    97.9  847.11   107.7  841.62   117.5  834.45   127.3  825.81   137.1  818.53
   166.5  800.34   176.3  795.04   186.1  790.37   195.9   786.3   215.4  779.27
   225.2  776.46     235  775.51   244.8  776.12   264.4  778.47     284  779.82
   342.8  781.03   401.5  783.14   430.9   784.9   499.4   788.1   528.8  789.92
   567.9  791.28   636.4  800.94   655.9  803.85   685.2   808.9   714.6  813.16
#Mann= 3 , 0 , 0
       0      .1       0   225.2    .045       0   244.8     .06       0
Bank Sta=225.2,244.8
XS Rating Curve= 0 ,0
Exp/Cntr=0.3,0.1

Type RM Length L Ch R = 1 ,4912.5  ,4932.4,4912.5,4883.2
XS GIS Cut Line= 3
     1675854.249      710325.102     1675281.863      710773.394
     1675169.042      710762.501
#Sta/Elev= 30
       0  876.56    19.6   868.1    88.4  839.96    98.2  835.11     167     796
   176.8   790.2   186.7  782.82   196.5  776.63   201.8   766.5   216.8   766.5
     226  775.88   245.6  777.56   275.1  778.98   284.9  779.04   304.6     780
   324.2  780.08   343.9     781     452  781.21   481.4  782.48   550.2  787.88
   569.8  788.93   589.5  789.45   599.3  791.09   609.1  793.65     619  796.82
   648.4  807.19   677.9  818.69     727  840.06   764.8   851.6   840.4  870.42
#Mann= 3 , 0 , 0
       0      .1       0   196.5    .045       0     226     .06       0
Bank Sta=196.5,226
XS Rating Curve= 0 ,0
Exp/Cntr=0.3,0.1